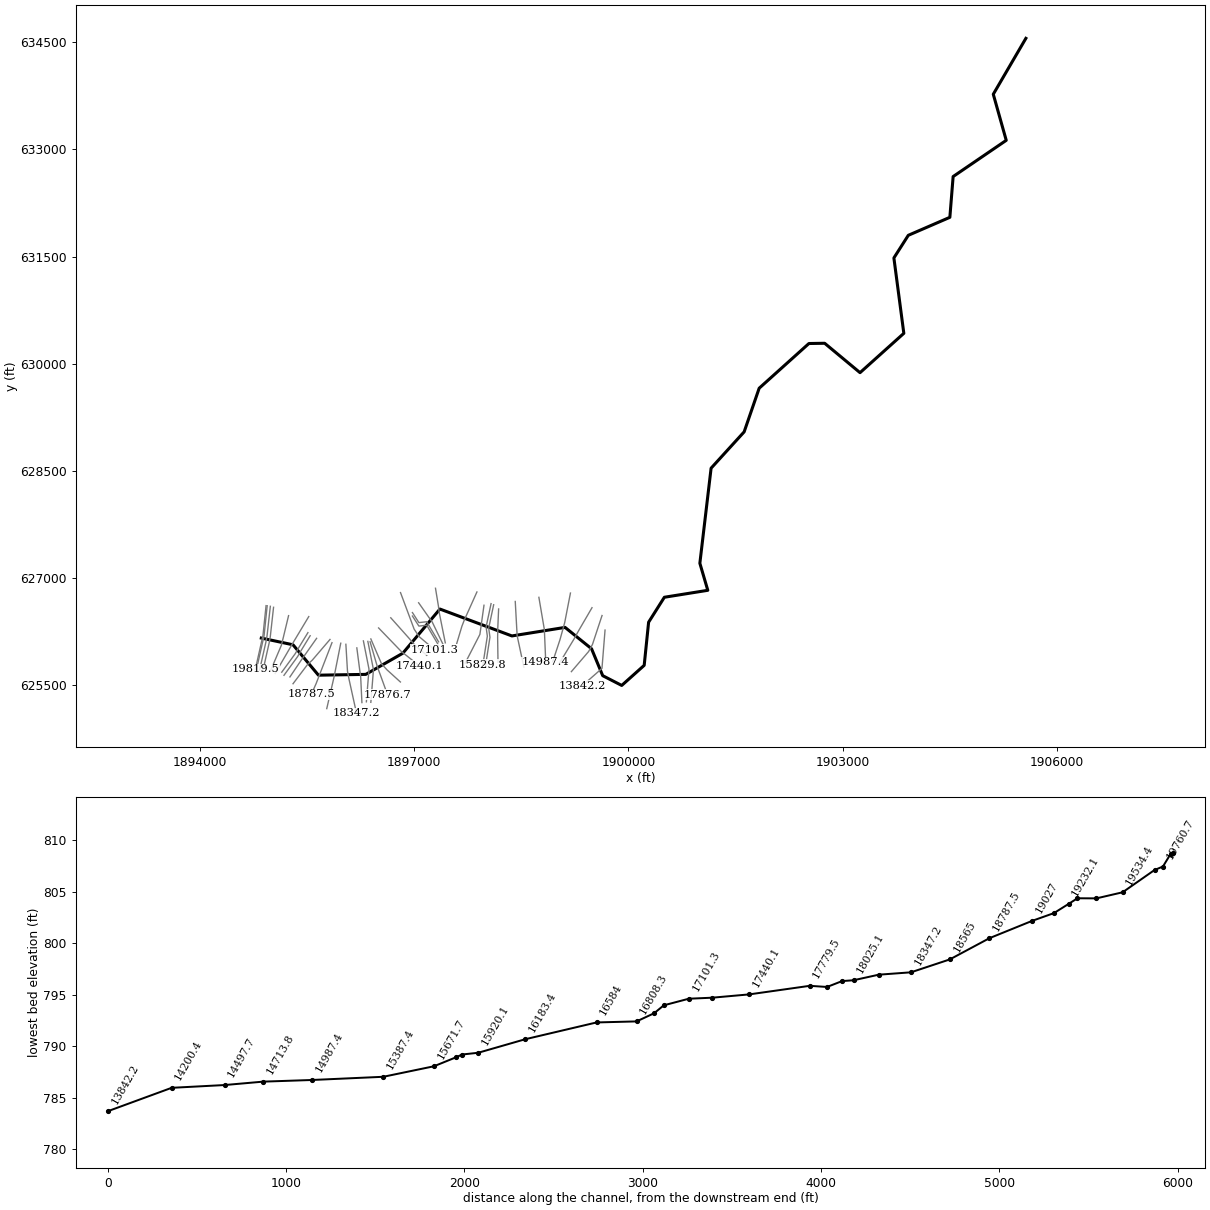
--- RushRun.prj (project) ---

Proj Title=RushRun
Current Plan=p01
Default Exp/Contr=0,0
English Units
Geom File=g01
Flow File=f01
Plan File=p01
BEGIN DESCRIPTION:
AMEC Environment & Infrastructure, 2013
Projection: NAD 1983 State Plane West Virginia South FIPS 4702 (US Feet)
Vertical Datum: NAVD 1988
END DESCRIPTION:
DSS Export Rating Curves= 0
DSS Export Rating Curve Sorted= 0
DSS Export Volume Flow Curves= 0
DXF OffsetX= 0
DXF OffsetY= 0
DXF ScaleX= 0
DXF ScaleY= 0

--- RushRun.p01 (plan) ---

Plan Title=Floodplain
Program Version=4.00
Geom File=g01
Flow File=f01
K Sum by GR=0
Std Step Tol=0.01
Critical Tol=0.01
Num of Std Step Trials=20
Max Error Tol=0.3
Flow Tol Ratio=0.001
Split Flow NTrial=30
Split Flow Tol=0.02
Split Flow Ratio=0.02
Log Output Level=0
Friction Slope Method=1
Unsteady Friction Slope Method=2
Unsteady Bridges Friction Slope Method=1
Global Log Level=0
CheckData=False
Run HTab=0
Run UNet=0
Run PostProcess=0
UNET Theta=0
UNET Theta Warmup=0
UNET ZTol=0
UNET ZSATol=0
UNET MxIter=0
UNET MaxInSteps=0
UNET DtIC=0
UNET DtMin=0
UNET MaxCRTS=0
UNET WFStab=0
UNET SFStab=0
UNET WFX=0
UNET SFX=0
UNET DSS MLevel=0
UNET DZMax Abort=0
UNET Convert EG Bridges=0
UNET Use Existing IB Tables=0
UNET Froude Limit=0
UNET Froude Power=0
Write IC File=0
Echo Input=False
Echo Output=False
Write Detailed=0

--- RushRun.f01 (steady flow) ---

Flow Title=NFF Regression Equation
Program Version=4.10
Number of Profiles= 1
Profile Names=P100yr
River Rch & RM=RushRun,Main            ,19819.5
924.2843
River Rch & RM=RushRun,Main            ,18565
950.5514
River Rch & RM=RushRun,Main            ,18347.2
1285.856
River Rch & RM=RushRun,Main            ,16584
1352.655
River Rch & RM=RushRun,Main            ,13663.6
1432.194
River Rch & RM=RushRun,Main            ,12991.1
 1498.04
River Rch & RM=RushRun,Main            ,9537.3
1603.289
River Rch & RM=RushRun,Main            ,9380.9
1742.249
River Rch & RM=RushRun,Main            ,4382.4
1842.508
River Rch & RM=RushRun,Main            ,4187
1898.923
River Rch & RM=RushRun,Main            ,166.5
1948.397
Boundary for River Rch & Prof#=RushRun,Main            , 1
Up Type= 0
Dn Type= 3
Dn Slope=0.00176
DSS Import GetInterval= 0
DSS Import GetPeak= 0
DSS Import FillOption= 0

--- RushRun.g01 (geometry) ---

Geom Title=USGS 3m DEM
Program Version=4.10

River Reach=RushRun         ,Main
Reach XY= 30
     1894860.664      626160.768     1895304.662      626066.657
     1895660.707      625641.167     1896323.563       625652.51
     1896841.682      625948.609     1897360.948      626566.906
      1898368.54      626190.464     1899112.733      626310.027
     1899483.265      626011.215     1899639.584      625634.346
     1899905.695      625497.538     1900220.247      625778.877
     1900282.155      626382.902     1900502.711      626731.994
     1901110.568       626829.27     1900999.405      627207.877
     1901156.701      628538.592     1901619.367      629047.109
     1901829.712      629657.907     1902525.911      630283.699
     1902746.478       630287.18     1903241.463      629875.585
     1903854.519      630426.153     1903715.392      631481.467
     1903917.001      631798.185     1904498.804      632050.031
     1904544.621      632620.702     1905288.033      633127.615
     1905106.616      633772.904     1905562.918      634555.386

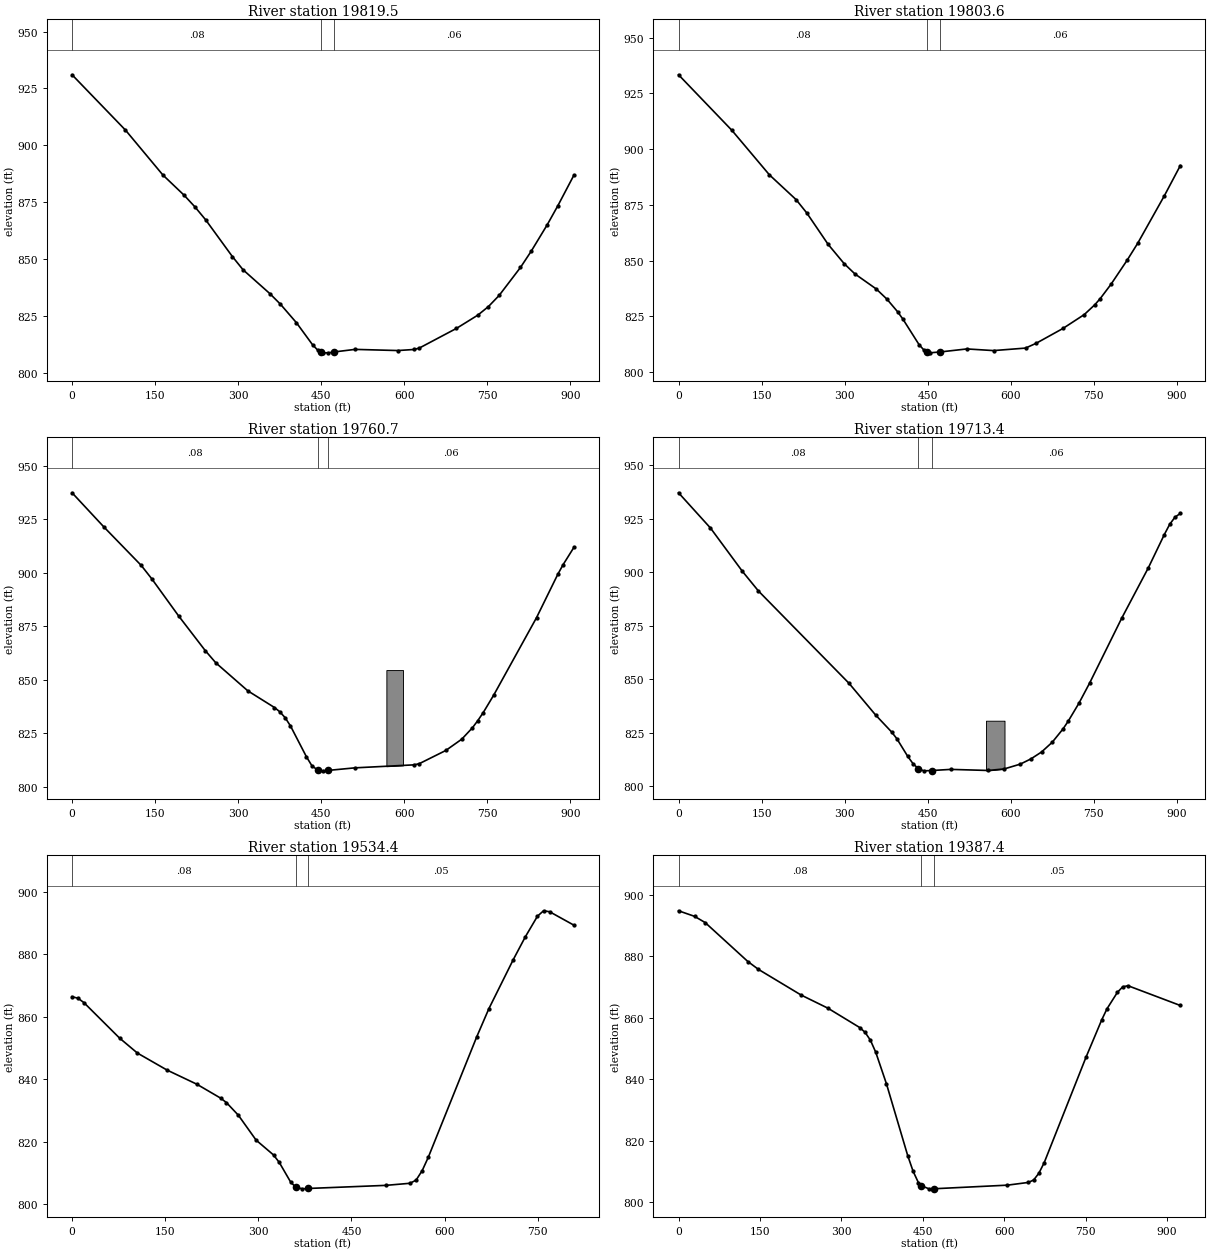
Type RM Length L Ch R = 1 ,19819.5 ,15.8,15.9,15.8
XS GIS Cut Line= 4
      1894927.49      626614.624     1894883.488      626192.163
     1894866.127      626117.294     1894777.151      625722.328
#Sta/Elev= 30
       0     931    96.5  906.66   164.1  886.91   202.7  877.96     222  872.88
   241.3  867.22   289.6  851.05   308.9  845.23   357.2  834.77   376.5  830.07
   405.4  821.93   434.4  812.27     444  809.84   449.7   809.2   453.6  808.76
   463.2   808.7   472.8  809.07   511.2  810.22   588.4  809.71   617.3  810.17
   626.9  810.75   694.4  819.45     733  825.28   752.2  829.06   771.5  833.94
   810.1  846.27   829.4  853.38   858.3  864.99   877.6  873.41   906.5   886.8
#Mann= 3 , 0 , 0
       0     .08       0   449.7    .045       0   472.8     .06       0
Bank Sta=449.7,472.8
XS Rating Curve= 0 ,0
Exp/Cntr=0.3,0.1

Type RM Length L Ch R = 1 ,19803.6 ,41.9,42.9,44.2
XS GIS Cut Line= 4
     1894943.115      626613.322     1894899.113      626190.861
     1894881.752      626115.991     1894792.776      625721.026
#Sta/Elev= 30
       0   933.3    96.5  908.37   164.1  888.46   212.4  877.33   231.7  871.35
   270.3  857.26   299.2  848.64   318.6  844.04   357.2  837.28   376.5  832.72
   395.8  827.06   405.4  823.74   434.4  812.37     444  809.71   448.7  809.19
   453.6  808.65   472.8  809.05   520.9   810.4   569.1  809.66   626.9  810.78
   646.2  812.95   694.4  819.57     733  825.81   752.2  830.25   761.9     833
   781.2  839.36   810.1  850.05   829.4  857.72   877.6  879.04   906.5   892.6
#Mann= 3 , 0 , 0
       0     .08       0   448.7    .045       0   472.8     .06       0
Bank Sta=448.7,472.8
XS Rating Curve= 0 ,0
Exp/Cntr=0.3,0.1

Type RM Length L Ch R = 1 ,19760.7 ,47.2,47.3,47.2
XS GIS Cut Line= 4
     1894987.252      626605.514     1894941.503      626194.478
     1894925.889      626108.183     1894836.913      625713.217
#Sta/Elev= 30
       0  937.37    57.7  921.33     125  903.39   144.3  897.04   192.4  879.82
   240.4  863.65   259.7  857.87   317.4  844.81   365.5  837.02   375.1  835.04
   384.7  832.28   394.3  828.46   423.3  813.95   433.1   809.8   443.5  807.77
   452.6  807.43   462.3  807.63   510.9  808.83     617  810.22   626.6  810.73
   674.8  816.94   703.7  822.23     723  827.57   732.6  830.89   742.3  834.59
   761.5  842.87   838.7  879.02   877.2  899.32   886.8  903.83   906.1  911.82
#Mann= 3 , 0 , 0
       0     .08       0   443.5    .045       0   462.3     .06       0
#Block Obstruct= 1 ,-1
  567.55  597.61  854.52
Bank Sta=443.5,462.3
XS Rating Curve= 0 ,0
Exp/Cntr=0.3,0.1

Type RM Length L Ch R = 1 ,19713.4 ,180.4,179,177.6
XS GIS Cut Line= 4
     1895032.391      626591.625     1894986.642      626180.589
     1894971.028      626094.294     1894882.052      625699.328
#Sta/Elev= 30
       0  937.15    57.7  920.65   115.4  900.38   144.3  891.21   307.8  848.05
   355.9   833.2   384.7  825.28   394.3  822.09   413.6  813.97   423.3  810.48
   432.7  808.18   442.8  807.09  457.04  807.23   491.5  807.77   559.1  807.26
     588  807.98     617  810.22   636.2  812.66   655.5   815.9   674.8  820.46
   694.1  826.63   703.7  830.33     723  838.71   742.3  848.13   800.1  878.41
   848.3  902.04   877.2   917.6   886.8  922.35   896.5  925.76   906.1  927.48
#Mann= 3 , 0 , 0
       0     .08       0   432.7    .045       0  457.04     .06       0
#Block Obstruct= 1 ,-1
  555.18  588.63  830.54
Bank Sta=432.7,457.04
XS Rating Curve= 0 ,0
Exp/Cntr=0.3,0.1

Type RM Length L Ch R = 1 ,19534.4 ,153.6,147,140.4
XS GIS Cut Line= 4
     1895242.501      626474.643     1895173.057      626186.449
     1895141.807      626059.713     1894992.501      625709.018
#Sta/Elev= 30
       0  866.42     9.6  865.93    19.1  864.53    76.5  853.18   105.2  848.39
     153  842.94   200.8  838.43   239.1  833.98   248.6  832.54   267.8  828.49
   296.4  820.52   324.4  815.78   333.7  813.38   352.4  806.97   360.7  805.43
     371  804.93   380.4  805.05   505.2  806.04   544.2  806.71     554  807.72
   563.8  810.74   573.6     815   651.8  853.64   671.3  862.62   710.4  878.25
   729.9  885.58   749.5   892.2   759.3  893.93     769  893.63   808.1  889.33
#Mann= 3 , 0 , 0
       0     .08       0   360.7    .045       0   380.4     .05       0
Bank Sta=360.7,380.4
XS Rating Curve= 0 ,0
Exp/Cntr=0.3,0.1

Type RM Length L Ch R = 1 ,19387.4 ,105.5,106.3,106.2
XS GIS Cut Line= 3
     1895524.972      626461.418     1895292.509      626073.949
     1895054.753      625665.246
#Sta/Elev= 30
       0  894.85    29.5  893.04    49.1  891.01   127.7  878.34   147.3  875.77
   225.9  867.42     275  863.17     334  856.83   343.8  855.27   353.6  852.72
   363.4  848.81   383.1  838.55   422.4  815.12   432.2  810.09     442  806.36
  447.52  805.37   461.5  804.34   471.2  804.37   606.2  805.54   644.8  806.43
   654.5  807.24   664.1  809.44   673.8  812.84     751  847.23   779.9  859.36
   789.6  862.96   808.9  868.34   818.5  870.08   828.2  870.46   924.7  864.02
#Mann= 3 , 0 , 0
       0     .08       0  447.52    .045       0   471.2     .05       0
Bank Sta=447.52,471.2
XS Rating Curve= 0 ,0
Exp/Cntr=0.3,0.1

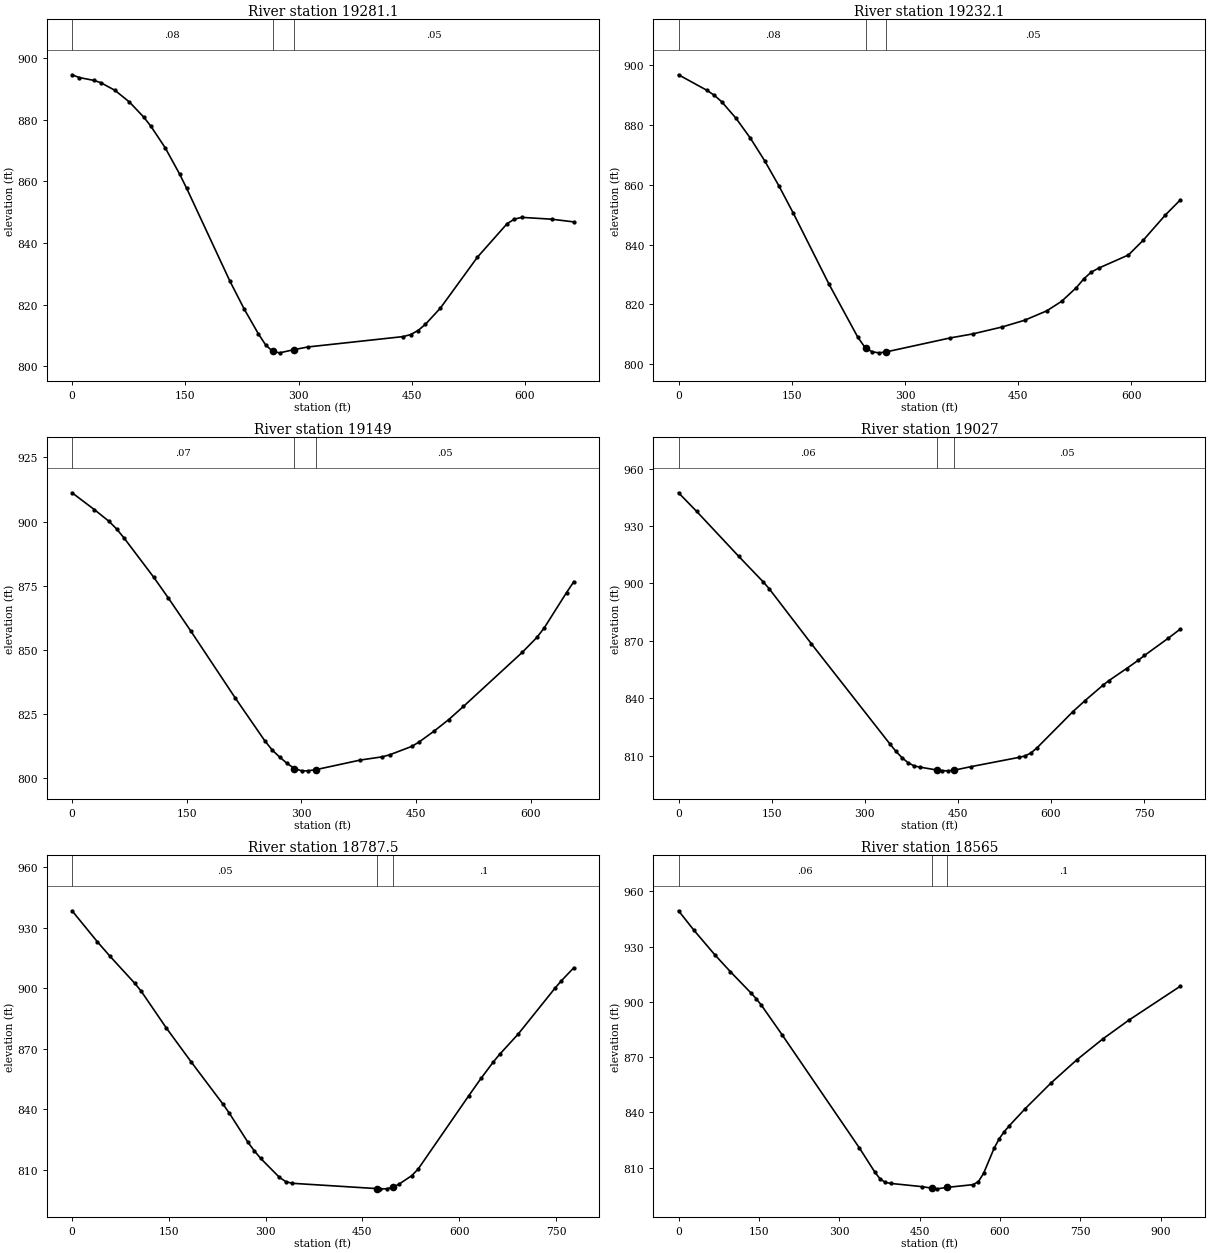
Type RM Length L Ch R = 1 ,19281.1 ,49.8,49,49.6
XS GIS Cut Line= 4
     1895513.335      626236.796     1895379.654      626018.046
     1895337.987      625945.129     1895147.015      625682.976
#Sta/Elev= 30
       0  894.54     9.5  893.64    28.5  892.74      38  891.99      57  889.46
      76   885.7      95  880.79   104.4  877.86   123.4  870.84   142.4  862.37
   151.9  857.66   208.9   827.7   227.9  818.61   246.9  810.47   256.4  806.93
   265.7  804.81     275  804.35   293.7  805.37   312.4  806.26   438.6  809.62
   448.5  810.28   458.3  811.59   468.1  813.62   487.8  818.83   536.9  835.36
   576.2  846.23     586  847.73   595.9  848.29   635.2   847.7   664.7  846.82
#Mann= 3 , 0 , 0
       0     .08       0   265.7    .045       0   293.7     .05       0
Bank Sta=265.7,293.7
XS Rating Curve= 0 ,0
Exp/Cntr=0.3,0.1

Type RM Length L Ch R = 1 ,19232.1 ,84.9,83.1,81.6
XS GIS Cut Line= 4
     1895544.585      626193.393     1895410.904      625974.643
     1895369.237      625901.726     1895178.265      625639.574
#Sta/Elev= 30
       0  896.72      38  891.47    47.5  889.84      57  887.76      76  882.23
      95   875.6   113.9  868.07   132.9  859.63   151.9  850.54   199.4  826.72
   237.4  809.07   246.9  805.64   248.7  805.36   256.4  804.15   265.7  803.81
     275  804.12     360   808.8   389.5  810.12   428.8  812.46   458.3  814.69
   487.8  817.84   507.4  821.02   527.1  825.63   536.9  828.55   546.7  830.78
   556.6  832.12   595.9   836.5   615.5  841.42     645   849.9   664.7  854.91
#Mann= 3 , 0 , 0
       0     .08       0   248.7    .045       0     275     .05       0
Bank Sta=248.7,275
XS Rating Curve= 0 ,0
Exp/Cntr=0.3,0.1

Type RM Length L Ch R = 1 ,19149   ,126.5,122,115.8
XS GIS Cut Line= 4
     1895634.862      626156.935     1895478.612      625934.713
     1895423.057      625856.588     1895261.599      625617.004
#Sta/Elev= 30
       0  911.23    29.1  904.69    48.5  900.06    58.2  897.16    67.9  893.66
   106.7  878.37   126.1  870.17   155.2  857.42   213.4  831.32   252.2  814.58
     262  810.95   271.7  808.23   281.2  805.83   290.8  803.81   300.4  802.92
   308.3  802.91   319.6  803.41   377.2  807.12     406  808.38   415.7  809.18
   444.6  812.46   454.2   814.2   473.4  818.35   492.7  822.87     512  828.01
     589   849.1   608.3  854.96   617.9  858.72   646.8  872.34   656.4  876.62
#Mann= 3 , 0 , 0
       0     .07       0   290.8    .045       0   319.6     .05       0
Bank Sta=290.8,319.6
XS Rating Curve= 0 ,0
Exp/Cntr=0.3,0.1

Type RM Length L Ch R = 1 ,19027   ,228.2,239.5,248.5
XS GIS Cut Line= 4
     1895822.362       626141.31     1895575.734      625853.201
     1895508.126      625790.615     1895305.001      625521.518
#Sta/Elev= 30
       0  947.37    29.2  937.64    97.2   914.1   136.1  900.95   145.9  897.34
   213.9  868.57   340.4  816.27   350.1  812.39   359.8  809.11   369.5   806.5
   379.2  804.78   388.5  804.12   416.1   802.6   425.3  802.24   434.5  802.16
   443.7  802.48   471.4  804.36   548.4  809.18   558.1  809.92   567.7  811.48
   577.3  814.08   635.1  832.98   654.4  838.68   683.3  846.73   692.9  849.16
   721.8  855.57   741.1  859.98   750.7   862.4   789.3  871.48   808.5   876.2
#Mann= 3 , 0 , 0
       0     .06       0   416.1    .045       0   443.7     .05       0
Bank Sta=416.1,443.7
XS Rating Curve= 0 ,0
Exp/Cntr=0.3,0.1

Type RM Length L Ch R = 1 ,18787.5 ,217.5,222.5,226.3
XS GIS Cut Line= 4
      1895850.14      626096.171     1895712.987      625742.004
     1895627.918      625523.254     1895561.946      625373.949
#Sta/Elev= 30
       0   938.4      39  923.11    58.4  915.98    97.4  902.35   107.1  898.52
   146.1  880.26     185  863.27   233.7  842.57   243.5  838.12   272.7  823.52
   282.4  819.36   292.2  815.61   321.4  806.16   331.1   804.1   340.8  803.24
  473.33  800.58   477.6  800.48   487.4  800.51   497.2  801.23   506.9  802.84
   526.5  807.04   536.3  810.27   614.5  846.52   633.7  855.22   652.9  863.43
   662.5  867.14   691.3   877.2   748.9  900.19   758.5  903.74   777.7  910.16
#Mann= 3 , 0 , 0
       0     .05       0  473.33    .045       0   497.2      .1       0
Bank Sta=473.33,497.2
XS Rating Curve= 0 ,0
Exp/Cntr=0.3,0.1

Type RM Length L Ch R = 1 ,18565   ,208.6,217.8,227.2
XS GIS Cut Line= 3
      1895972.86      626088.676     1895878.913      625615.517
     1895776.946      625173.072
#Sta/Elev= 30
       0  949.49    28.9  938.87    67.5  925.65    96.5  916.48   135.1  904.85
   144.7  901.81   154.4  898.28     193  882.24   337.7  820.56   366.6  807.38
   376.3  803.78   385.9  801.97   395.6  801.38   453.4  799.64   472.8  798.79
   482.4  798.42   501.7  799.22     550  800.71   559.7  802.38   569.3  806.85
   588.7  820.34   598.3   825.6     608  829.53   617.6  832.82   646.6  841.88
   694.9  855.89   743.2  868.52   791.5  879.81   839.8  889.96   936.4  908.52
#Mann= 3 , 0 , 0
       0     .06       0   472.8    .045       0   501.7      .1       0
Bank Sta=472.8,501.7
XS Rating Curve= 0 ,0
Exp/Cntr=0.3,0.1

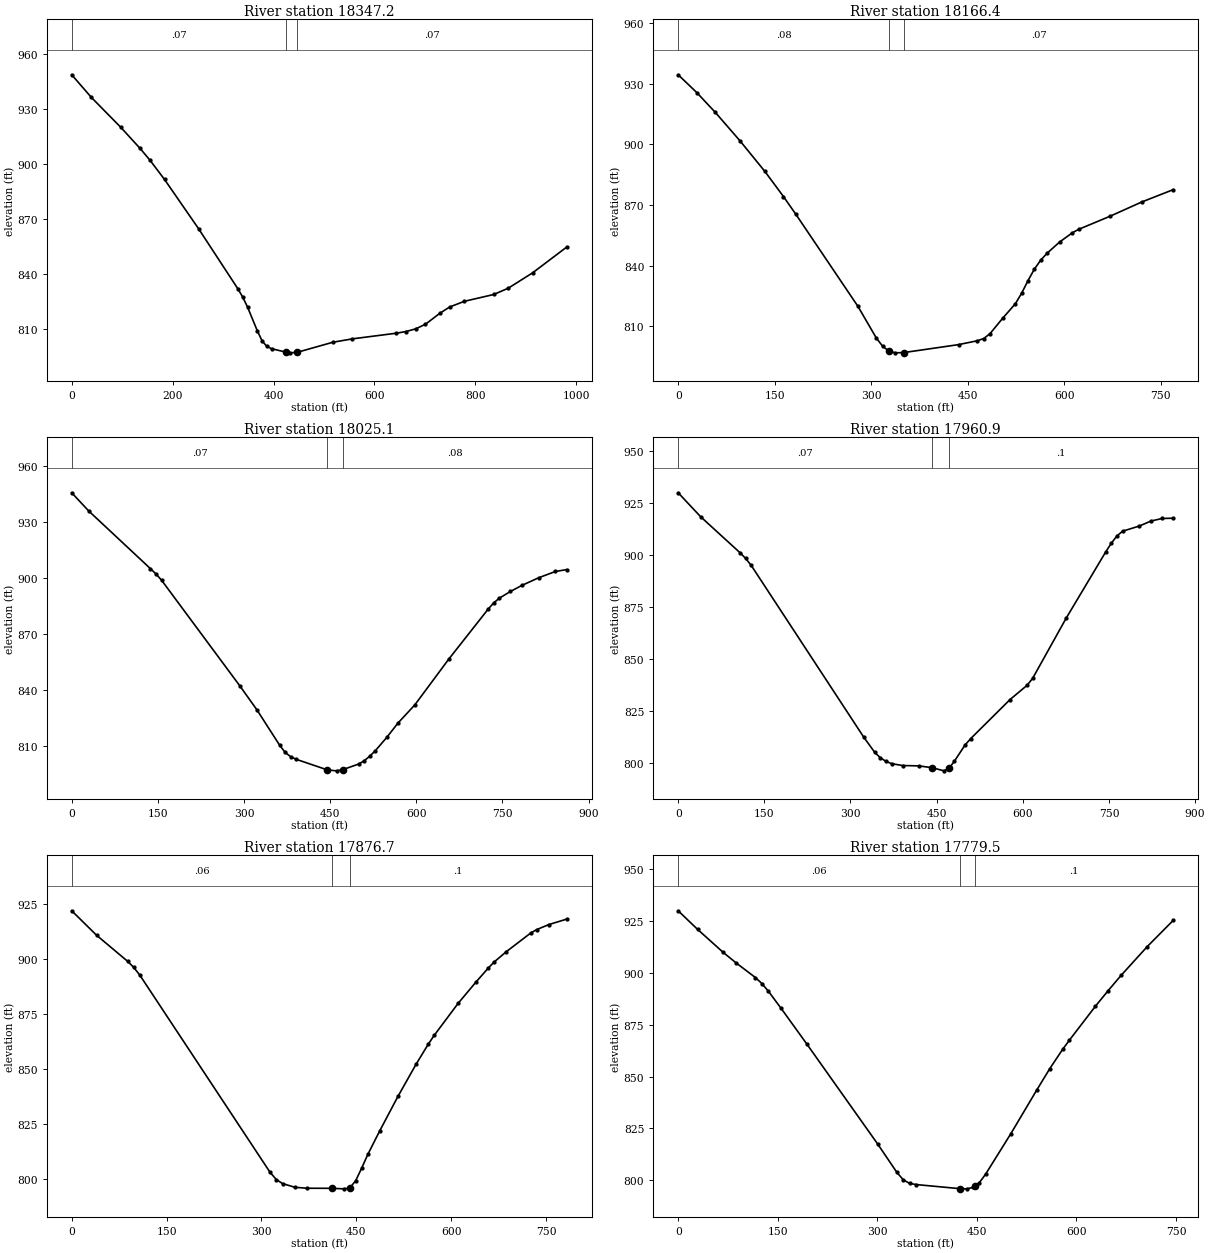
Type RM Length L Ch R = 1 ,18347.2 ,181.2,180.8,179.4
XS GIS Cut Line= 4
     1896044.585      626073.601     1896067.154      625696.865
     1896087.987       625587.49      1896193.89      625106.588
#Sta/Elev= 30
       0  948.45    38.7  936.21    96.8  919.99   135.5  908.38   154.8  902.08
   183.9  891.51   251.6  864.63     329  832.15   338.7  827.62   348.4  822.13
   367.7  809.24   377.4  803.64   386.7  800.69     396  799.42   423.8   797.6
   433.1  797.17   447.5   797.5   517.7  802.94   556.3  804.78   643.2  807.84
   662.6  808.77   681.9  810.24   701.2  812.73   730.1  818.78   749.4  822.16
   778.4  825.21   836.4  828.91   865.3  832.34   913.6  840.71   981.2  854.74
#Mann= 3 , 0 , 0
       0     .07       0   423.8    .045       0   447.5     .07       0
Bank Sta=423.8,447.5
XS Rating Curve= 0 ,0
Exp/Cntr=0.3,0.1

Type RM Length L Ch R = 1 ,18166.4 ,141.5,141.3,136.9
XS GIS Cut Line= 4
     1896197.905      626023.363     1896237.836      625717.807
     1896251.724      625620.585     1896269.086      625257.738
#Sta/Elev= 30
       0  934.44    28.9  925.64    57.8  915.81    96.3   901.7   134.8  886.63
   163.7  874.21     183  865.41   279.3  819.99   308.2  804.18     318  800.14
   327.8  797.78   337.6  796.94  350.65  797.07   435.8     801   465.3  802.93
   475.1  804.02   484.9  806.46   504.5  814.07   524.2  821.21     534  826.44
   543.8  832.63   553.6  838.26   563.4  842.69   573.3  846.13   592.9  851.72
   612.5  856.25   622.4  857.98   671.4  864.49   720.5  871.51   769.6  877.64
#Mann= 3 , 0 , 0
       0     .08       0   327.8    .045       0  350.65     .07       0
Bank Sta=327.8,350.65
XS Rating Curve= 0 ,0
Exp/Cntr=0.3,0.1

Type RM Length L Ch R = 1 ,18025.1 ,64.7,64.2,64.6
XS GIS Cut Line= 4
      1896289.81       626120.91     1896367.935      625727.681
     1896361.425       625639.14     1896331.586      625268.154
#Sta/Elev= 30
       0  945.73    29.3  936.04   136.9  905.02   146.7  902.14   156.4  898.78
   293.4  841.73   322.7  829.04   361.8  810.26   371.6  806.29   381.4  803.94
   391.1  802.57   445.3  796.88   461.1   796.4   471.9  797.05   499.5  800.04
   509.3  801.83   519.1  804.31   528.9   807.3   548.5  814.36     568  822.04
   597.4  831.83   656.2  856.28   724.8  883.16   734.6  886.56   744.4  889.11
   763.9  892.74   783.5  895.94   812.9  900.08   842.3  903.48   861.9  904.47
#Mann= 3 , 0 , 0
       0     .07       0   445.3    .045       0   471.9     .08       0
Bank Sta=445.3,471.9
XS Rating Curve= 0 ,0
Exp/Cntr=0.3,0.1

Type RM Length L Ch R = 1 ,17960.9 ,74,84.2,93.7
XS GIS Cut Line= 4
      1896352.31      626113.966     1896430.435      625720.737
     1896423.925      625632.195     1896394.086       625261.21
#Sta/Elev= 30
       0  929.84    39.1  918.33   107.6  901.07   117.3  898.35   127.1  894.98
   322.7  812.64   342.2  805.18     352   802.6   361.8  800.85   371.6  799.76
   391.1  798.86   418.7  798.71   441.1  797.87   463.1  796.32   471.9   797.7
   480.8   800.9   499.5  808.75   509.3   811.8   577.8  830.56   607.2  837.33
     617  840.67   675.8  869.76   744.4  901.46   754.1  905.61   763.9  909.11
   773.7  911.39   803.1  913.89   822.7  916.22   842.3   917.5   861.9  917.63
#Mann= 3 , 0 , 0
       0     .07       0   441.1    .045       0   471.9      .1       0
Bank Sta=441.1,471.9
XS Rating Curve= 0 ,0
Exp/Cntr=0.3,0.1

Type RM Length L Ch R = 1 ,17876.7 ,89,97.2,105.8
XS GIS Cut Line= 4
     1896383.669      626108.432     1896487.836      625750.793
     1896527.766      625643.154     1896628.461      625365.377
#Sta/Elev= 30
       0  922.03    39.2  910.94    88.2  899.13      98  896.33   107.8  892.75
   313.7  803.22   323.5  799.98   333.3  798.15   352.9  796.45   372.5  796.02
   410.8  795.99   429.9  795.75   439.5   796.1     449  799.43   458.6   805.2
   468.2  811.37   487.3  822.22   515.9  837.75   544.5  852.32   563.6  861.34
   573.1  865.42   611.2  880.05   639.8  889.85   658.9  896.08   668.4  898.88
   687.5  903.52   725.6  911.88   735.1  913.46   754.2  915.74   782.8  918.25
#Mann= 3 , 0 , 0
       0     .06       0   410.8    .045       0   439.5      .1       0
Bank Sta=410.8,439.5
XS Rating Curve= 0 ,0
Exp/Cntr=0.3,0.1

Type RM Length L Ch R = 1 ,17779.5 ,334.4,339.4,343.6
XS GIS Cut Line= 4
     1896394.086      626148.363     1896543.391       625801.14
     1896619.332      625716.885     1896807.714      625545.932
#Sta/Elev= 30
       0  929.87    29.1  920.94    67.8  909.82    87.2  904.76   116.3   897.7
     126  894.82   135.7  891.18   155.1  882.82   193.8  865.65   300.4  817.52
   329.5  803.78   339.2  800.17   348.9  798.46   358.6  797.92   425.2  795.92
   434.7  795.86   444.1  796.52   446.5  797.09   453.6  798.78     463  802.86
   501.2  822.46   540.3  843.53   559.9  853.82   579.4  863.18   589.2  867.43
   628.4  883.79   647.9  891.43   667.5  898.81   706.6  912.59   745.8  925.24
#Mann= 3 , 0 , 0
       0     .06       0   425.2    .045       0   446.5      .1       0
Bank Sta=425.2,446.5
XS Rating Curve= 0 ,0
Exp/Cntr=0.3,0.1

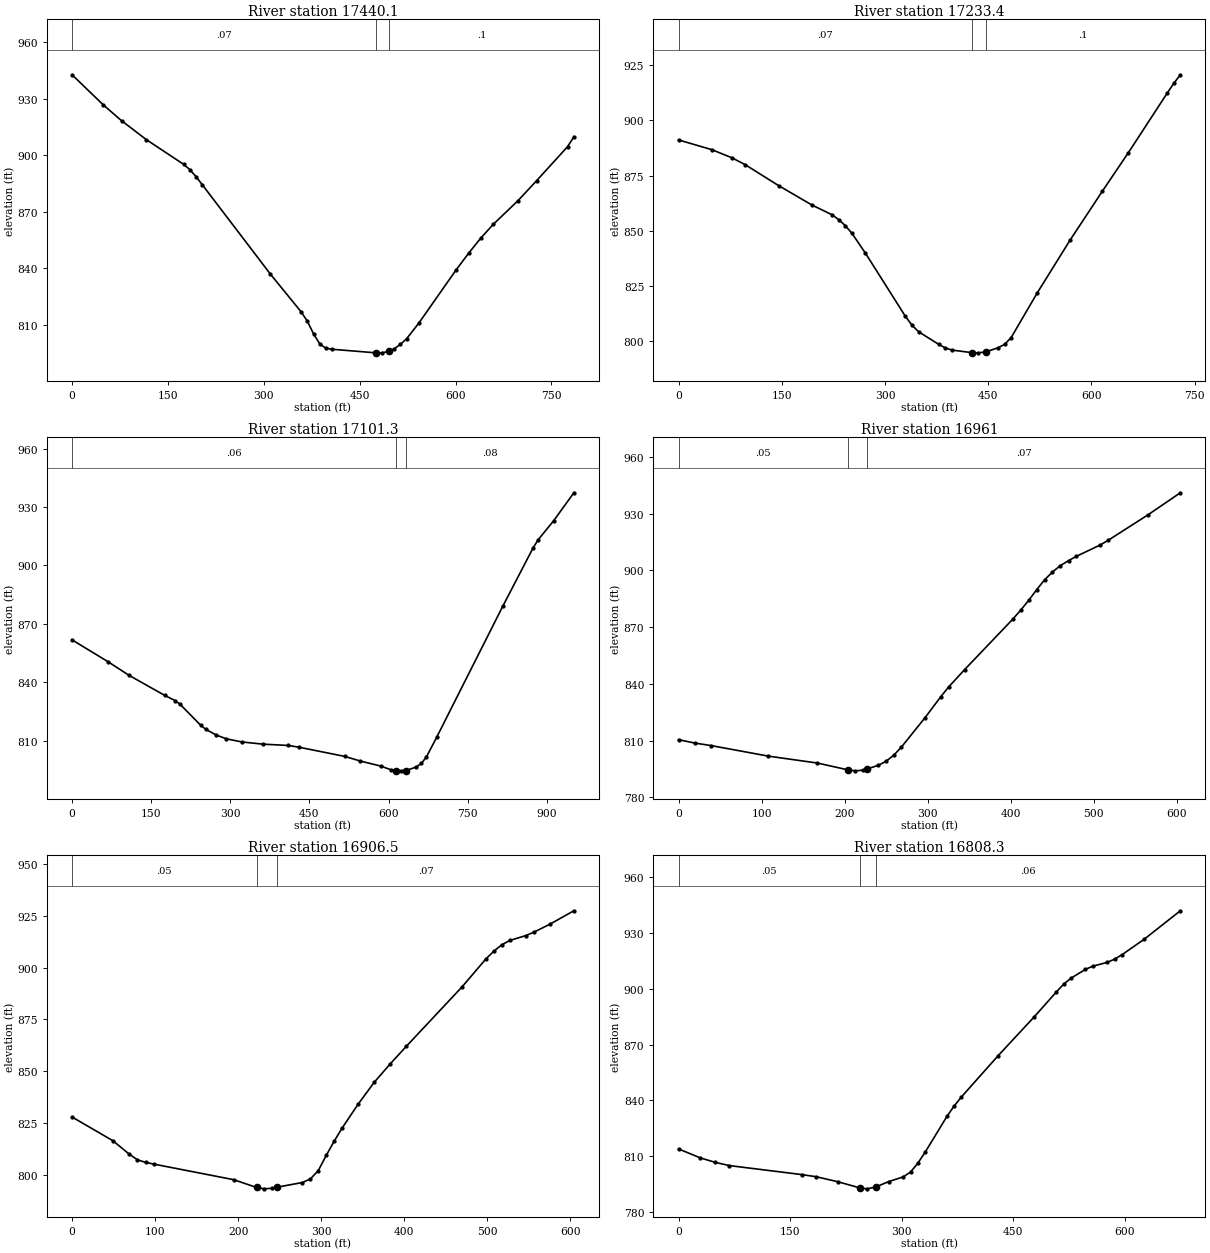
Type RM Length L Ch R = 1 ,17440.1 ,210.5,206.7,201.4
XS GIS Cut Line= 3
     1896502.648      626302.399     1896818.789      625974.654
     1897076.811      625769.456
#Sta/Elev= 30
       0  942.78    48.4  926.92    77.5  918.36   116.3  908.29   174.4  895.22
   184.1  892.43   193.8   888.7   203.5  884.45     310  836.98   358.5  816.75
   368.2  811.75   377.9  805.03   387.6  799.72   397.2  797.44   406.9  796.92
   474.8  795.05   484.5  795.03   495.7  795.76   503.8  797.12   513.6  799.52
   523.2  802.46   542.6  810.89   600.8   839.1   620.2  847.86   639.6  856.09
     659  863.33   697.8  875.96   726.9  886.56   775.3  904.66     785  909.84
#Mann= 3 , 0 , 0
       0     .07       0   474.8    .045       0   495.7      .1       0
Bank Sta=474.8,495.7
XS Rating Curve= 0 ,0
Exp/Cntr=0.3,0.1

Type RM Length L Ch R = 1 ,17233.4 ,134.8,132.1,129.6
XS GIS Cut Line= 4
     1896673.165       626444.37     1896924.901      626162.252
     1897011.707      626060.255     1897176.638      625919.196
#Sta/Elev= 30
       0  891.16    48.5  886.73    77.6  883.06      97  879.92   145.4  870.47
   193.9  861.66     223  857.26   232.7  855.08   242.4  852.31   252.1  848.78
   271.5  839.89   329.6  811.26   339.3  807.19     349  804.24   378.1  798.54
   387.7  796.94   397.2  795.96   425.9  794.82   435.5  794.71   446.9  795.16
   464.2  797.01   473.8  798.54   483.3  801.63   521.5  822.02   568.6  845.62
   615.8  867.93   653.6  885.38   710.2  912.44   719.6  916.78   729.1  920.67
#Mann= 3 , 0 , 0
       0     .07       0   425.9    .045       0   446.9      .1       0
Bank Sta=425.9,446.9
XS Rating Curve= 0 ,0
Exp/Cntr=0.3,0.1

Type RM Length L Ch R = 1 ,17101.3 ,115.4,140.3,166.4
XS GIS Cut Line= 4
      1896809.45      626797.234     1897000.422      626285.081
     1897069.867      626180.915     1897283.408      626000.359
#Sta/Elev= 30
       0  861.82    68.3   850.6   107.4  843.72   175.7  833.32   195.2  830.68
     205  828.73     244  817.96   253.8  815.88   273.3  812.98   292.8  811.03
   322.1  809.43   361.2  808.32     410  807.62   429.5  806.78   517.3     802
   546.6  799.63   585.1  797.07   604.4  795.17     614  794.71   623.6  794.61
   633.3  794.78   652.5  796.57   662.2  798.39   671.8  801.73   691.1  811.73
   816.4  878.96   874.3  909.12   883.9  913.26   912.9  922.89   951.4  937.31
#Mann= 3 , 0 , 0
       0     .06       0     614    .045       0   633.3     .08       0
Bank Sta=614,633.3
XS Rating Curve= 0 ,0
Exp/Cntr=0.3,0.1

Type RM Length L Ch R = 1 ,16961   ,54.1,54.5,54.1
XS GIS Cut Line= 4
     1896976.117      626469.109     1897066.395      626328.484
      1897175.77      626340.637     1897342.436      626059.387
#Sta/Elev= 30
       0  810.44    19.7  808.64    39.3  807.32   108.1  801.75   167.1   798.1
   203.8  794.51     213  793.97   222.1  794.32     227  794.94   240.5  796.89
   249.6  798.96   258.8  802.11     268  806.35   296.4  821.87   315.6  833.08
   325.2  838.32   344.5  847.53   402.2  874.06   411.8  878.83   421.4  884.03
     431  889.63   440.6  894.92   450.2   899.1   459.8   902.5   469.5  905.08
   479.1  907.39   507.9  913.42   517.5   915.9   565.6  929.43   604.1  940.96
#Mann= 3 , 0 , 0
       0     .05       0   203.8    .045       0     227     .07       0
Bank Sta=203.8,227
XS Rating Curve= 0 ,0
Exp/Cntr=0.3,0.1

Type RM Length L Ch R = 1 ,16906.5 ,122.8,98.2,72.9
XS GIS Cut Line= 4
     1896976.117       626517.72     1897066.395      626377.095
      1897175.77      626389.248     1897342.436      626107.998
#Sta/Elev= 30
       0  827.89    49.2  816.42    68.8  809.96    78.6  807.26    88.5  805.98
    98.3  805.15   194.6  797.62   222.1  793.86   231.3   793.2   240.5  793.47
   246.8  794.01   277.2  796.24   286.8  797.95   296.4     802     306  809.35
   315.6  816.25   325.2  822.61   344.5  834.15   363.7  844.63   382.9   853.5
   402.2  861.95   469.5  890.75   498.3  904.29   507.9  908.04   517.5  911.12
   527.2   913.2   546.4  915.53     556  917.18   575.2  921.01   604.1   927.5
#Mann= 3 , 0 , 0
       0     .05       0   222.1    .045       0   246.8     .07       0
Bank Sta=222.1,246.8
XS Rating Curve= 0 ,0
Exp/Cntr=0.3,0.1

Type RM Length L Ch R = 1 ,16808.3 ,235.5,224.3,211.5
XS GIS Cut Line= 4
     1897062.922      626654.873     1897186.186      626479.526
     1897253.895       626384.04       1897403.2      626075.012
#Sta/Elev= 30
       0  813.88    29.2  809.07    48.7  806.73    68.2  804.92   165.6  800.08
   185.1  798.92   214.3  796.22   243.6  792.93   253.4  792.41   265.1   793.4
   282.6  796.32   302.1  798.85   311.9  801.46   321.6  806.12   331.4  812.03
   360.8  831.34   370.6  837.02   380.4  841.87   429.4  863.91   478.5  885.06
   507.9  898.28   517.7  902.48   527.5  905.68   547.1  910.48   556.9  912.14
   576.5  914.24   586.4  915.98   596.2  918.34   625.6  926.53   674.6  941.96
#Mann= 3 , 0 , 0
       0     .05       0   243.6    .045       0   265.1     .06       0
Bank Sta=243.6,265.1
XS Rating Curve= 0 ,0
Exp/Cntr=0.3,0.1

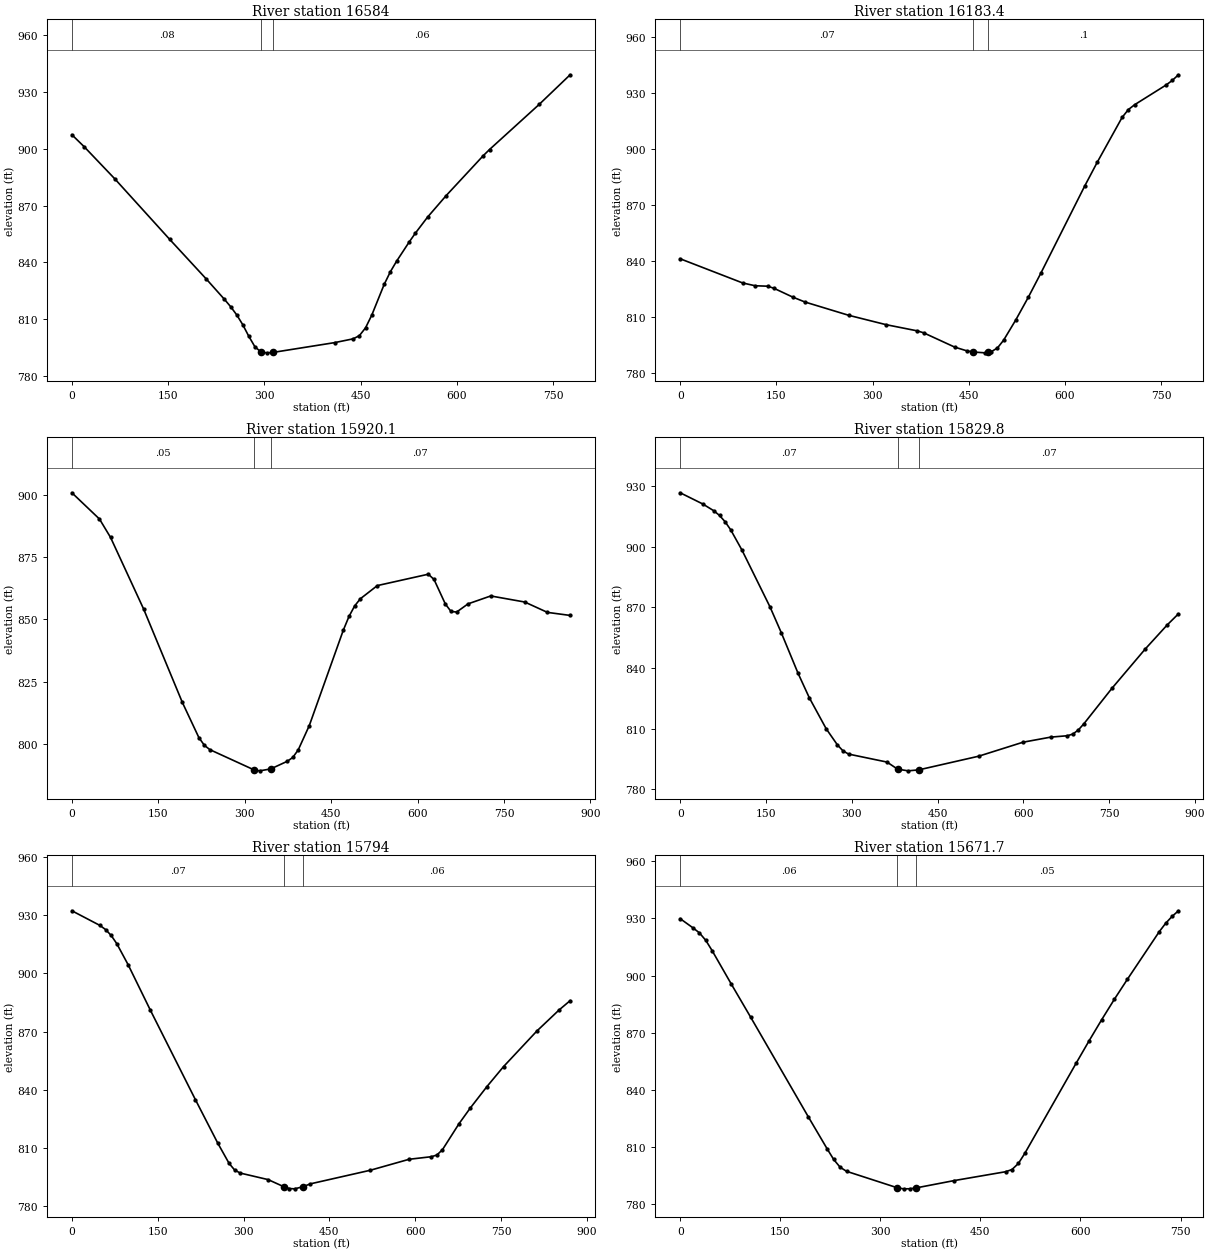
Type RM Length L Ch R = 1 ,16584   ,411.2,400.6,389.5
XS GIS Cut Line= 4
     1897299.033      626857.998       1897340.7      626604.526
      1897348.82      626529.761     1897436.186      626094.109
#Sta/Elev= 30
       0   907.4      19  901.12    66.6  884.22   152.2  852.26   209.3  831.32
   237.8  820.51   247.4  816.66   256.9  812.32   266.3  807.14   275.7  801.03
   285.1  795.57   294.5  792.77   303.9  792.31   313.3  792.53   409.4   797.7
   438.3   799.7     448  801.38   457.6   805.5   467.3   812.2   486.6  828.39
   496.3  835.11     506  840.68   525.3  850.64   534.9  855.31   554.2  863.91
   583.2  875.27   641.2  896.42   650.8   899.6   728.1  923.38   776.4  939.04
#Mann= 3 , 0 , 0
       0     .08       0   294.5    .045       0   313.3     .06       0
Bank Sta=294.5,313.3
XS Rating Curve= 0 ,0
Exp/Cntr=0.3,0.1

Type RM Length L Ch R = 1 ,16183.4 ,258.1,263.3,268.9
XS GIS Cut Line= 4
     1897878.895      626805.915     1897703.547       626415.29
     1897668.825      626326.748     1897595.908      626083.693
#Sta/Elev= 30
       0  841.04    97.3  828.11   116.8   826.6   136.2  826.37     146  825.28
   175.2  820.58   194.6  817.89   262.7  810.79   321.1  805.76   369.8  802.44
   379.5  801.42   428.2  793.73   447.2  791.73   456.7  791.12   475.7  790.68
  480.62  791.02   485.2  791.29   494.8  793.32   504.3  797.41   523.3  808.27
   542.8  820.39   562.3  833.24   630.6  879.84   650.2  892.62   689.2  916.77
     699  920.96   708.7  923.54   757.5  934.04   767.3  936.51     777  939.57
#Mann= 3 , 0 , 0
       0     .07       0   456.7    .045       0  480.62      .1       0
Bank Sta=456.7,480.62
XS Rating Curve= 0 ,0
Exp/Cntr=0.3,0.1

Type RM Length L Ch R = 1 ,15920.1 ,82.9,90.2,96.2
XS GIS Cut Line= 4
     1897977.853      626620.151     1897937.922      626335.429
     1897920.561      626212.165     1897713.964      625809.387
#Sta/Elev= 30
       0  900.73    47.9  890.21    67.1  882.85   124.6  854.12   191.7  816.77
   220.4  802.68     230  799.57   239.6  797.84   316.2  789.75   325.8  789.37
     345  790.13   373.7  793.18   383.3  794.72   392.8  797.75     412  807.49
     471  845.67   480.9  851.19   490.7   855.4   500.6  858.28   530.1  863.56
   618.6  868.12   628.5  866.01   648.2  856.16     658   853.2   667.8  852.97
   687.5  856.24   726.9  859.41   785.9  856.98   825.3  852.83   864.7  851.61
#Mann= 3 , 0 , 0
       0     .05       0   316.2    .045       0     345     .07       0
Bank Sta=316.2,345
XS Rating Curve= 0 ,0
Exp/Cntr=0.3,0.1

Type RM Length L Ch R = 1 ,15829.8 ,36.5,35.8,35.8
XS GIS Cut Line= 4
     1898076.811       626642.72     1898007.367      626316.331
     1898024.728      626187.859     1897962.228      625785.081
#Sta/Elev= 30
       0  926.57    39.3  921.06    58.9  917.66    68.7  915.37    78.5  912.26
    88.3  908.26     108  898.24     157  870.18   176.7  857.44   206.1  837.34
   225.7  825.29   255.2  809.98   274.8  802.02   284.6  799.05   294.4  797.47
   361.5  793.53     380  790.03   398.5   789.2     417  789.68   521.6  796.42
   599.2  803.34   647.7  805.86   676.8  806.54   686.5  807.39   696.2  809.46
     706  812.58   754.5  829.91   812.7  849.33   851.5  861.35   870.9  866.76
#Mann= 3 , 0 , 0
       0     .07       0     380    .045       0     417     .07       0
Bank Sta=380,417
XS Rating Curve= 0 ,0
Exp/Cntr=0.3,0.1

Type RM Length L Ch R = 1 ,15794   ,125.8,122.3,118.7
XS GIS Cut Line= 4
      1898113.27      626627.095     1898043.825      626300.706
     1898061.186      626172.234     1897998.686      625769.456
#Sta/Elev= 30
       0  932.27    49.1   924.7    58.9  922.58    68.7  919.54    78.5   915.3
    98.2  904.52   137.4  880.89   215.9   834.9   255.2  812.36   274.8  802.03
   284.6  798.58   294.4  797.04     343  793.68   370.7  789.98     380  789.08
   389.2  788.92  403.52  789.98     417   791.5   521.6   798.5   589.5  804.16
   628.3  805.48     638  806.36   647.7  809.08   676.8  822.55   696.2  830.51
   725.4  841.61   754.5  851.93   812.7  870.26   851.5  881.11   870.9  885.93
#Mann= 3 , 0 , 0
       0     .07       0   370.7    .045       0  403.52     .06       0
Bank Sta=370.7,403.52
XS Rating Curve= 0 ,0
Exp/Cntr=0.3,0.1

Type RM Length L Ch R = 1 ,15671.7 ,282.5,284.3,289.2
XS GIS Cut Line= 4
     1898182.714      626568.068     1898170.561       626290.29
     1898168.825      626167.026     1898174.033       625821.54
#Sta/Elev= 30
       0   929.9    19.2  925.07    28.8  922.46    38.4  918.49    47.9   913.1
    76.7   895.5   105.5  878.25   191.8     826   220.5  808.92   230.1  803.47
   239.7  799.41   249.3  797.27   325.5  788.61   334.9  788.06   344.4   788.1
   353.9  788.57   410.9  792.41   487.7  797.04   497.3   798.2   506.9  801.38
   516.5  806.67   593.3  853.92   612.5  865.55   631.7  876.83   650.9  887.66
   670.1  897.98     718  923.05   727.6  927.46   737.2  931.07   746.8  934.05
#Mann= 3 , 0 , 0
       0     .06       0   325.5    .045       0   353.9     .05       0
Bank Sta=325.5,353.9
XS Rating Curve= 0 ,0
Exp/Cntr=0.3,0.1

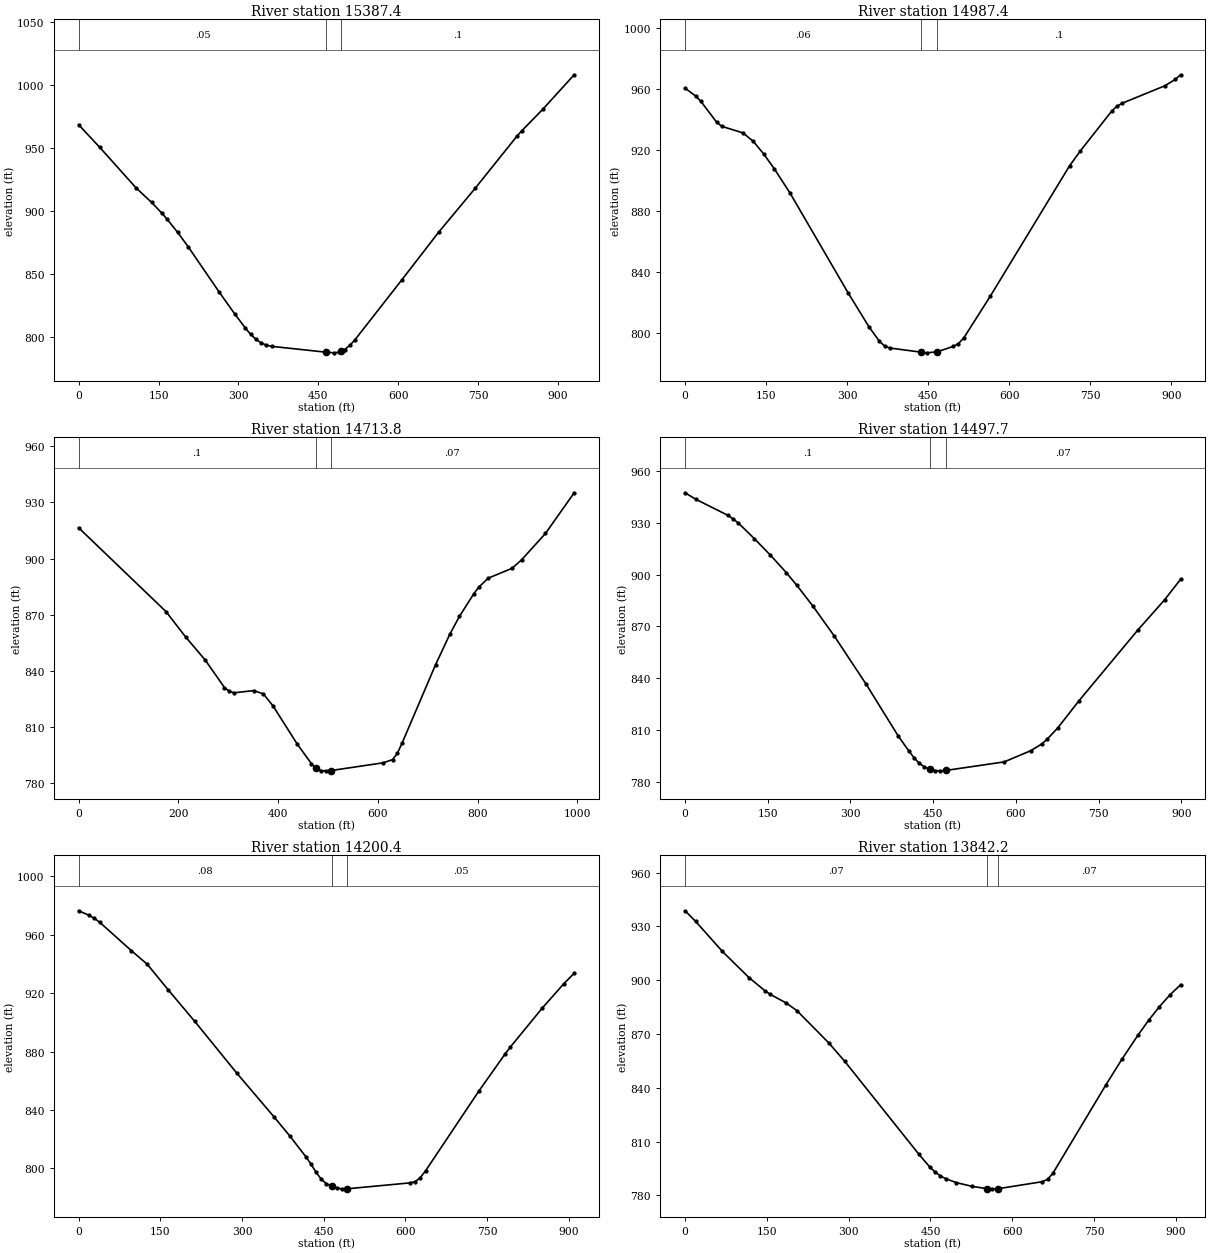
Type RM Length L Ch R = 1 ,15387.4 ,397.3,400,395.5
XS GIS Cut Line= 3
     1898415.521      626672.952     1898441.765      626193.907
     1898536.204      625753.283
#Sta/Elev= 30
       0  968.53    39.2  950.74   107.7  918.34   137.1  906.67   156.7  897.98
   166.4  893.22     186  882.84   205.6   871.5   264.4   835.1   293.7  817.64
   313.3  806.64   323.1  801.66   332.9  797.78   342.7  794.99   352.5  793.16
   362.3  792.21  464.89  787.54   479.8  787.04   489.6  787.59  493.39  788.39
   499.4  789.64   509.2  793.04     519  797.52   607.1  845.27   675.7  882.89
   744.3  917.83   822.6  959.24   832.4  963.87   871.6  980.88   930.4 1008.27
#Mann= 3 , 0 , 0
       0     .05       0  464.89    .045       0  493.39      .1       0
Bank Sta=464.89,493.39
XS Rating Curve= 0 ,0
Exp/Cntr=0.3,0.1

Type RM Length L Ch R = 1 ,14987.4 ,283.4,273.6,266.6
XS GIS Cut Line= 3
     1898746.243      626730.933     1898822.783      626280.384
     1898842.354      625820.413
#Sta/Elev= 30
       0  960.58    19.4   955.5    29.2  951.97    58.3   938.3    68.1  935.52
     107  931.25   126.4  925.66   145.8  917.26   165.3  907.59   194.5  891.57
   301.4  826.36   340.3  803.88   359.8   794.3   369.5  791.18   379.2   789.9
   437.6  787.13   447.3  786.73   466.8  787.41   496.2  790.92     506  792.76
   515.8  796.45   564.8  823.83   711.7  909.57   731.3  919.18     790  945.68
   799.8   948.8   809.6  950.79     888  962.16   907.6  966.41   917.4  969.42
#Mann= 3 , 0 , 0
       0     .06       0   437.6    .045       0   466.8      .1       0
Bank Sta=437.6,466.8
XS Rating Curve= 0 ,0
Exp/Cntr=0.3,0.1

Type RM Length L Ch R = 1 ,14713.8 ,220,216.1,212.2
XS GIS Cut Line= 4
     1899187.922      626790.724     1899108.061      626379.265
     1899042.089      626139.682     1898939.658       625830.22
#Sta/Elev= 30
       0  916.47   175.4  871.61   214.4  858.16   253.4  845.92   292.4   831.1
   302.2  829.04   311.9  828.29   350.9  829.44   370.4  827.69   389.9  821.23
   438.2  800.91   466.9  790.37   475.1  788.13     486  786.66   495.6  786.57
   505.2  786.69   610.3  790.84   629.4  792.54     639  795.91   648.5  801.35
   715.6  843.24   744.3  859.57   763.5  869.09   792.3  881.16   801.9   884.6
     821   889.5     869  894.79   888.2  899.34   936.1  913.44   993.6  935.16
#Mann= 3 , 0 , 0
       0      .1       0   475.1    .045       0   505.2     .07       0
Bank Sta=475.1,505.2
XS Rating Curve= 0 ,0
Exp/Cntr=0.3,0.1

Type RM Length L Ch R = 1 ,14497.7 ,298.1,297.3,295.7
XS GIS Cut Line= 4
     1899489.779       626585.86     1899300.285      626260.229
     1899235.231       626142.72     1899034.711      625810.689
#Sta/Elev= 30
       0  947.42    19.3  943.67    77.3   934.4    86.9  932.34    96.6  929.88
   125.6  920.86   154.6  911.33   183.6  901.16   202.9   893.7   231.8  881.75
   270.5  864.46   328.4  836.48   386.4  806.56   405.5  797.93   415.1  793.93
   424.7  790.66   434.3  788.52   443.9  787.09   453.5  786.38   463.1  786.24
   472.7  786.46     579  791.43   627.4  797.98   646.8  801.76   656.5  804.46
   675.9  811.05   714.7  826.92   821.4  867.89   869.9  885.37     899  897.31
#Mann= 3 , 0 , 0
       0      .1       0   443.9    .045       0   472.7     .07       0
Bank Sta=443.9,472.7
XS Rating Curve= 0 ,0
Exp/Cntr=0.3,0.1

Type RM Length L Ch R = 1 ,14200.4 ,365.1,358.2,350.6
XS GIS Cut Line= 4
     1899630.218       626476.28     1899496.082      626071.106
     1899442.263      625972.147     1899200.943      625690.897
#Sta/Elev= 30
       0  976.42    19.4  973.28    29.1  971.18    38.8  968.51      97  949.06
   126.1  939.75   164.9  922.08   213.4   900.6     291  864.97   358.9  835.21
     388  822.07   417.1  808.05   426.8  802.86   436.2  797.19   445.6  792.55
     455   789.5   464.4   787.9   473.7  786.56   483.1  785.97   492.5  785.98
   607.7  790.02   617.5  790.83   627.2  793.54     637  798.26   734.5  852.68
   783.3  878.42     793  883.18   851.5  909.82   890.5  926.26     910  933.64
#Mann= 3 , 0 , 0
       0     .08       0   464.4    .045       0   492.5     .05       0
Bank Sta=464.4,492.5
XS Rating Curve= 0 ,0
Exp/Cntr=0.3,0.1

Type RM Length L Ch R = 1 ,13842.2 ,160.1,178.7,200.8
XS GIS Cut Line= 4
     1899672.297      626272.495     1899629.403      625737.798
     1899577.679      625690.897     1899350.249      625491.245
#Sta/Elev= 30
       0  938.73    19.5  932.76    68.3  916.09     117  901.53   146.3  894.17
     156  892.18   185.3  887.33   204.8  883.13   263.3  865.14   292.6  854.87
   429.1  802.86   448.6  795.94   458.4   793.1   468.1  790.94   477.9  789.37
   497.4  787.18   526.7  785.06   553.9  783.78   562.6   783.7   573.6  783.75
     655  787.67   664.8  788.98   674.6  792.38   772.2  841.86   801.5   856.1
   830.8  869.46   850.3  877.72   869.8  885.21   889.3  891.84   908.9  897.52
#Mann= 3 , 0 , 0
       0     .07       0   553.9    .045       0   573.6     .07       0
Bank Sta=553.9,573.6
XS Rating Curve= 0 ,0
Exp/Cntr=0.3,0.1