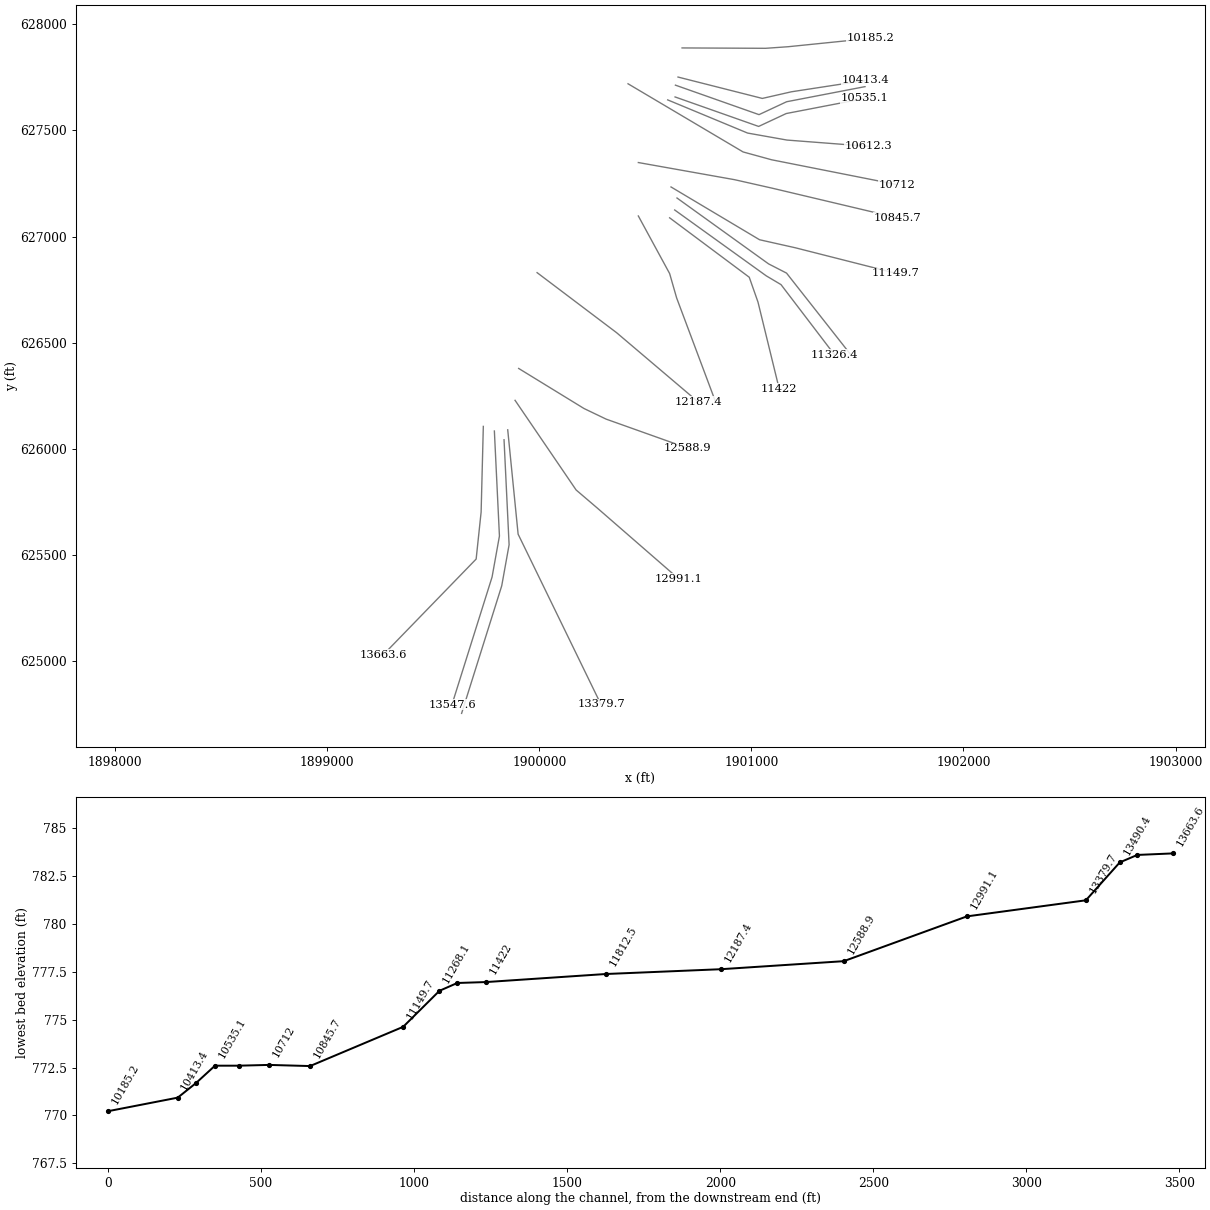
HEC-RAS study RushRun.prj: RushRun

--- RushRun.g01 (geometry) --- (continued)

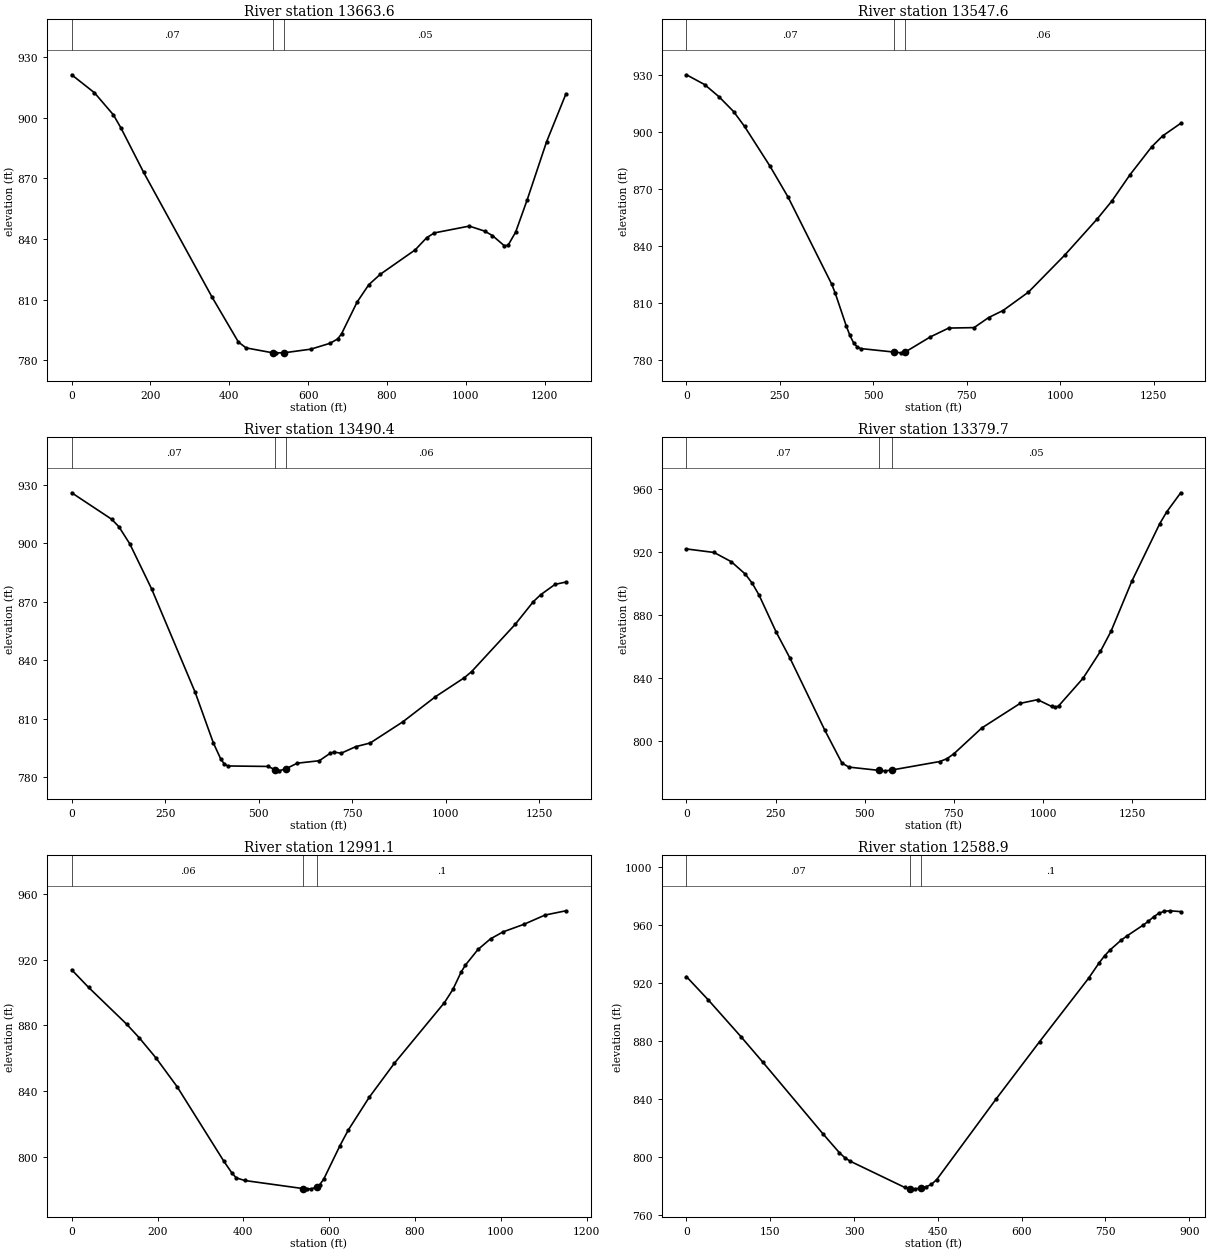
Type RM Length L Ch R = 1 ,13663.6 ,117.6,115.9,110.1
XS GIS Cut Line= 4
     1899736.208      626105.394     1899725.791      625701.748
     1899702.354      625480.394     1899264.854      625029.873
#Sta/Elev= 30
       0  921.13    57.7  912.26   105.8  901.34     125  894.84   182.7  872.86
   355.7  811.42   423.1  789.03   442.5  786.14   510.2   783.7  519.72  783.69
   539.3  783.72     607  785.51   655.8  788.42   675.4  790.61   685.2  793.22
   724.5  808.83   753.9  817.34   783.4  822.54   871.7  834.57   901.1  840.63
   920.7  842.98  1009.1  846.34  1048.3  843.84  1067.9  841.64  1097.4  836.72
  1107.2  836.75  1126.8  843.38  1156.2  859.43  1205.3  888.05  1254.4   911.7
#Mann= 3 , 0 , 0
       0     .07       0   510.2    .045       0   539.3     .05       0
Bank Sta=510.2,539.3
XS Rating Curve= 0 ,0
Exp/Cntr=0.3,0.1

Type RM Length L Ch R = 1 ,13547.6 ,58.9,57.2,55.5
XS GIS Cut Line= 4
     1899788.291      626083.693     1899812.163      625588.901
     1899777.441      625395.759     1899588.204       624794.63
#Sta/Elev= 30
       0   929.9    48.6  924.75    87.4  918.29   126.3  910.51   155.4  902.72
   223.4  881.83     272  865.47   388.5  819.72   398.2  814.84   427.4  797.75
   437.1  792.78   446.8  788.95   456.5   786.7   466.2  785.86   554.2  784.03
   573.9  783.61   583.7  783.88   652.4  792.01   701.3  796.64   769.2  796.88
     808  802.15   846.7  805.88   914.6  815.56  1011.6  835.01  1098.8  854.11
  1137.6  863.46  1186.1  877.29  1244.2     892  1273.3  897.71  1321.8  904.35
#Mann= 3 , 0 , 0
       0     .07       0   554.2    .045       0   583.7     .06       0
Bank Sta=554.2,583.7
XS Rating Curve= 0 ,0
Exp/Cntr=0.3,0.1

Type RM Length L Ch R = 1 ,13490.4 ,96.5,110.7,121.4
XS GIS Cut Line= 4
     1899833.864       626042.46     1899857.736      625547.668
     1899823.013      625354.526     1899633.777      624753.397
#Sta/Elev= 30
       0  925.97   106.8   912.4   126.3  908.53   155.4  899.74   213.7  876.65
   330.2  823.55   378.8  797.58   398.2  789.48     408  786.76   417.7  785.72
   524.8  785.48   544.4  783.79   554.2  783.22   573.9  784.37   603.3  787.15
   662.2  788.41   691.6  792.28   701.3  792.85   720.7  792.26   759.5  795.62
   798.3  797.51   885.5  808.37   972.8  821.27  1050.3  831.06  1069.7   834.2
  1186.1  858.43  1234.6  870.07    1254   873.6  1292.7  878.95  1321.8  880.15
#Mann= 3 , 0 , 0
       0     .07       0   544.4    .045       0   573.9     .06       0
Bank Sta=544.4,573.9
XS Rating Curve= 0 ,0
Exp/Cntr=0.3,0.1

Type RM Length L Ch R = 1 ,13379.7 ,378,388.6,400.8
XS GIS Cut Line= 4
     1899851.225      626089.335      1899900.27      625597.581
     1899952.354      625490.811     1900290.895      624795.498
#Sta/Elev= 30
       0  922.21    77.5  919.96     126  914.06   164.7   906.3   184.1  900.55
   203.5  892.97   251.9  869.29   290.7   852.7   387.6  807.28     436  786.23
   455.4  783.62   539.9  781.53   558.2  781.24   576.4  781.78   710.9  787.17
   730.5  788.94     750  792.05   828.4  808.47     936   824.1     985  826.44
  1024.1  822.15  1033.9  821.52  1043.7  822.44  1112.2  839.99  1161.2  857.16
  1190.6  869.77  1249.3  901.74  1327.6  938.29  1347.2  945.79  1386.3  957.88
#Mann= 3 , 0 , 0
       0     .07       0   539.9    .045       0   576.4     .05       0
Bank Sta=539.9,576.4
XS Rating Curve= 0 ,0
Exp/Cntr=0.3,0.1

Type RM Length L Ch R = 1 ,12991.1 ,396.3,402.2,408
XS GIS Cut Line= 4
     1899885.839      626228.224     1900173.708      625805.915
     1900274.998      625719.511     1900658.083      625386.644
#Sta/Elev= 30
       0   913.8    39.3  903.11   127.8  880.76   157.3  872.42   196.6  860.07
   245.7  842.58   353.8  797.52   373.5  789.99   383.3  787.12     403  785.48
   539.6  780.54   549.1   780.4   558.6   780.4   571.5  781.59   577.7  782.86
   587.2  786.27   625.2  806.74   644.2  816.07     693  836.04   751.6  856.78
   868.7  893.87   888.2  901.81   907.7  912.54   917.5  916.68   946.8   926.2
     976  932.67  1005.3  936.91  1054.1  941.54  1102.9  947.14  1151.7  949.75
#Mann= 3 , 0 , 0
       0     .06       0   539.6    .045       0   571.5      .1       0
Bank Sta=539.6,571.5
XS Rating Curve= 0 ,0
Exp/Cntr=0.3,0.1

Type RM Length L Ch R = 1 ,12588.9 ,405.9,401.5,395.7
XS GIS Cut Line= 4
     1899902.875      626378.397     1900211.034      626189.595
     1900315.201      626139.682     1900699.316      626002.963
#Sta/Elev= 30
       0  924.53    39.1  908.46    97.7  883.04   136.8  865.46   244.2  816.08
   273.5  803.11   283.3  799.59     293  797.15   390.3  779.11   399.9  778.16
   409.5  778.06   419.2  778.52   428.8  779.49   438.4  781.09     448  784.49
   554.6  840.27   632.2  879.74   719.6  923.35     739  934.26   748.7  939.06
   758.4  943.05   777.8  949.65   787.6  952.43   816.7  959.93   826.4  962.63
   836.1  965.82   845.8  968.36   855.5  969.65   865.2     970   884.6  969.41
#Mann= 3 , 0 , 0
       0     .07       0   399.9    .045       0   419.2      .1       0
Bank Sta=399.9,419.2
XS Rating Curve= 0 ,0
Exp/Cntr=0.3,0.1

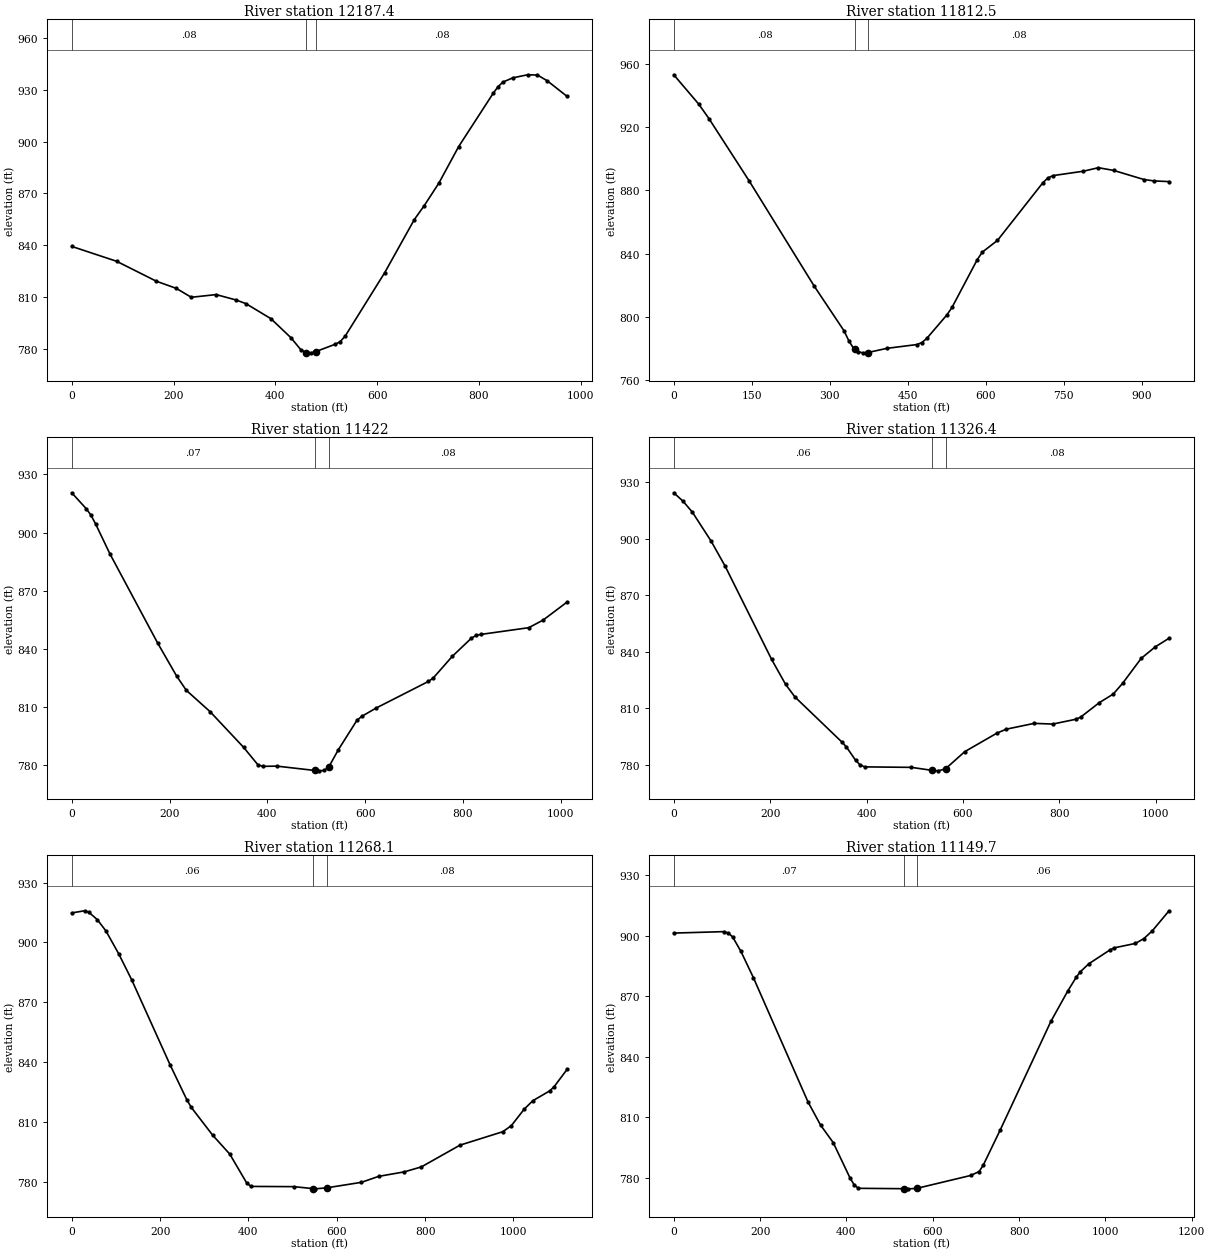
Type RM Length L Ch R = 1 ,12187.4 ,389.1,374.9,362
XS GIS Cut Line= 3
      1899989.68      626829.786     1900364.612       626546.87
     1900748.547      626221.306
#Sta/Elev= 30
       0  839.31    88.1   830.7   166.4  819.12   205.5  814.99   234.8  809.83
   283.8  811.39   322.9  808.26   342.5  806.11   391.4  797.41   430.6  786.41
   450.1  779.43   459.9  777.76   469.7  777.64   479.4  778.35   518.1  782.67
   527.8  784.21   537.5  787.47   614.9   824.1     673  854.84   692.4  862.88
   721.4  876.03   760.1  897.12   827.9  927.99   837.6  931.86   847.2  934.54
   866.6  936.99   895.6  938.76     915  938.61   934.4  935.24   973.1  926.26
#Mann= 3 , 0 , 0
       0     .08       0   459.9    .045       0   479.4     .08       0
Bank Sta=459.9,479.4
XS Rating Curve= 0 ,0
Exp/Cntr=0.3,0.1

Type RM Length L Ch R = 1 ,11812.5 ,389.5,390.5,391.2
XS GIS Cut Line= 4
     1900467.111      627096.713      1900614.68      626825.446
     1900647.694      626710.629     1900831.694      626219.977
#Sta/Elev= 30
       0  952.95    48.2  934.34    67.6   925.3   144.8  886.03   270.2  819.42
   327.2  791.38   336.4  785.12   345.6  780.25   348.7   779.5   354.8  778.01
     364  777.39   373.1  777.58   409.9  780.23   467.1  782.61   476.8  783.81
   486.5   786.5   525.3   801.4     535  806.09   583.5  836.22   593.2  840.97
   622.4  848.38   709.7   884.8   719.4  887.83   729.1  889.29   787.3  892.05
   816.4  894.28   845.6  892.58   903.8  886.83   923.2  885.94   952.3  885.51
#Mann= 3 , 0 , 0
       0     .08       0   348.7    .045       0   373.1     .08       0
Bank Sta=348.7,373.1
XS Rating Curve= 0 ,0
Exp/Cntr=0.3,0.1

Type RM Length L Ch R = 1 ,11422   ,79.6,95.5,111.5
XS GIS Cut Line= 4
      1900614.68      627088.033     1900990.114      626808.085
     1901031.347      626690.897     1901131.173      626282.911
#Sta/Elev= 30
       0  920.51    29.3  912.38      39  909.08    48.8  904.43      78     889
   175.6  842.95   214.6  825.82   234.2  818.55   282.9   807.5   351.2  789.15
   380.5  780.13   390.3  779.29   419.5   779.4     497  777.16   506.5  776.97
   516.1  777.17   525.6     779   544.8  787.76     583  803.02   592.6  805.03
   621.8  809.32   729.3  823.13   739.1   824.9   778.1   836.1   817.2  845.49
     827  846.92   836.8  847.41   934.4  850.87   963.7   854.8  1012.6  864.08
#Mann= 3 , 0 , 0
       0     .07       0     497    .045       0   525.6     .08       0
Bank Sta=497,525.6
XS Rating Curve= 0 ,0
Exp/Cntr=0.3,0.1

Type RM Length L Ch R = 1 ,11326.4 ,57.7,58.3,59.4
XS GIS Cut Line= 4
     1900638.552      627124.925     1901070.409      626814.595
     1901139.854      626773.363      1901391.59      626443.502
#Sta/Elev= 30
       0  924.35    19.3  919.86    38.7  914.03    77.4  898.75   106.4  885.52
     203  835.99   232.1  822.72   251.4  816.08   348.1  792.35   357.8  789.71
   377.1  782.57   386.8  779.97   396.4  779.02   493.1  778.76  536.72  777.14
   548.9  776.92   563.9  778.03   603.6  787.08   670.5  796.93   689.8  799.01
   747.7  802.09   786.3  801.72   834.5  804.29   844.2  805.42   882.8  813.08
   911.7  817.62     931  823.28   969.6  836.52   998.6  842.61  1027.5  847.22
#Mann= 3 , 0 , 0
       0     .06       0  536.72    .045       0   563.9     .08       0
Bank Sta=536.72,563.9
XS Rating Curve= 0 ,0
Exp/Cntr=0.3,0.1

Type RM Length L Ch R = 1 ,11268.1 ,116.6,118.4,123.3
XS GIS Cut Line= 4
     1900649.402      627181.349      1901081.26      626871.019
     1901165.895      626827.616     1901471.885      626439.161
#Sta/Elev= 30
       0  914.83      29   915.9    38.7  915.16      58  911.44    77.4   905.8
   106.4   894.3   135.4  881.45   222.4   838.8   261.1  820.93   270.7  817.33
   319.1   803.4   357.8  793.91   396.4  779.35   406.1  777.72   502.8  777.61
  545.64  776.64   550.8  776.51   577.1  777.01     656  779.78   694.8  782.76
     753  785.02   791.7  787.52     879  798.41     976  805.15   995.4  808.21
  1024.4  816.45  1043.8  820.66  1082.6  825.68  1092.3  827.75  1121.4  836.36
#Mann= 3 , 0 , 0
       0     .06       0  545.64    .045       0   577.1     .08       0
Bank Sta=545.64,577.1
XS Rating Curve= 0 ,0
Exp/Cntr=0.3,0.1

Type RM Length L Ch R = 1 ,11149.7 ,299.4,304.1,305.1
XS GIS Cut Line= 4
     1900621.191      627233.432     1901038.725      626984.734
     1901207.128      626946.974     1901681.086      626826.748
#Sta/Elev= 30
       0  901.22   116.6  901.94   126.4  901.19   136.1  899.41   155.5   892.2
   184.7  879.06     311  817.65   340.2  806.15   369.4  797.52   408.2  780.08
     418  776.59   427.7  774.89   533.9   774.7   543.5  774.63   562.7  774.84
   687.9  781.25   707.5  783.19   717.2  786.42   756.4   803.8   873.7   857.5
   912.8  872.54   932.4  879.34   942.2  882.13   961.7  886.04  1010.6  892.89
  1020.4  893.91  1069.3  896.09  1088.9  898.44  1108.4  902.26  1147.5  912.26
#Mann= 3 , 0 , 0
       0     .07       0   533.9    .045       0   562.7     .06       0
Bank Sta=533.9,562.7
XS Rating Curve= 0 ,0
Exp/Cntr=0.3,0.1

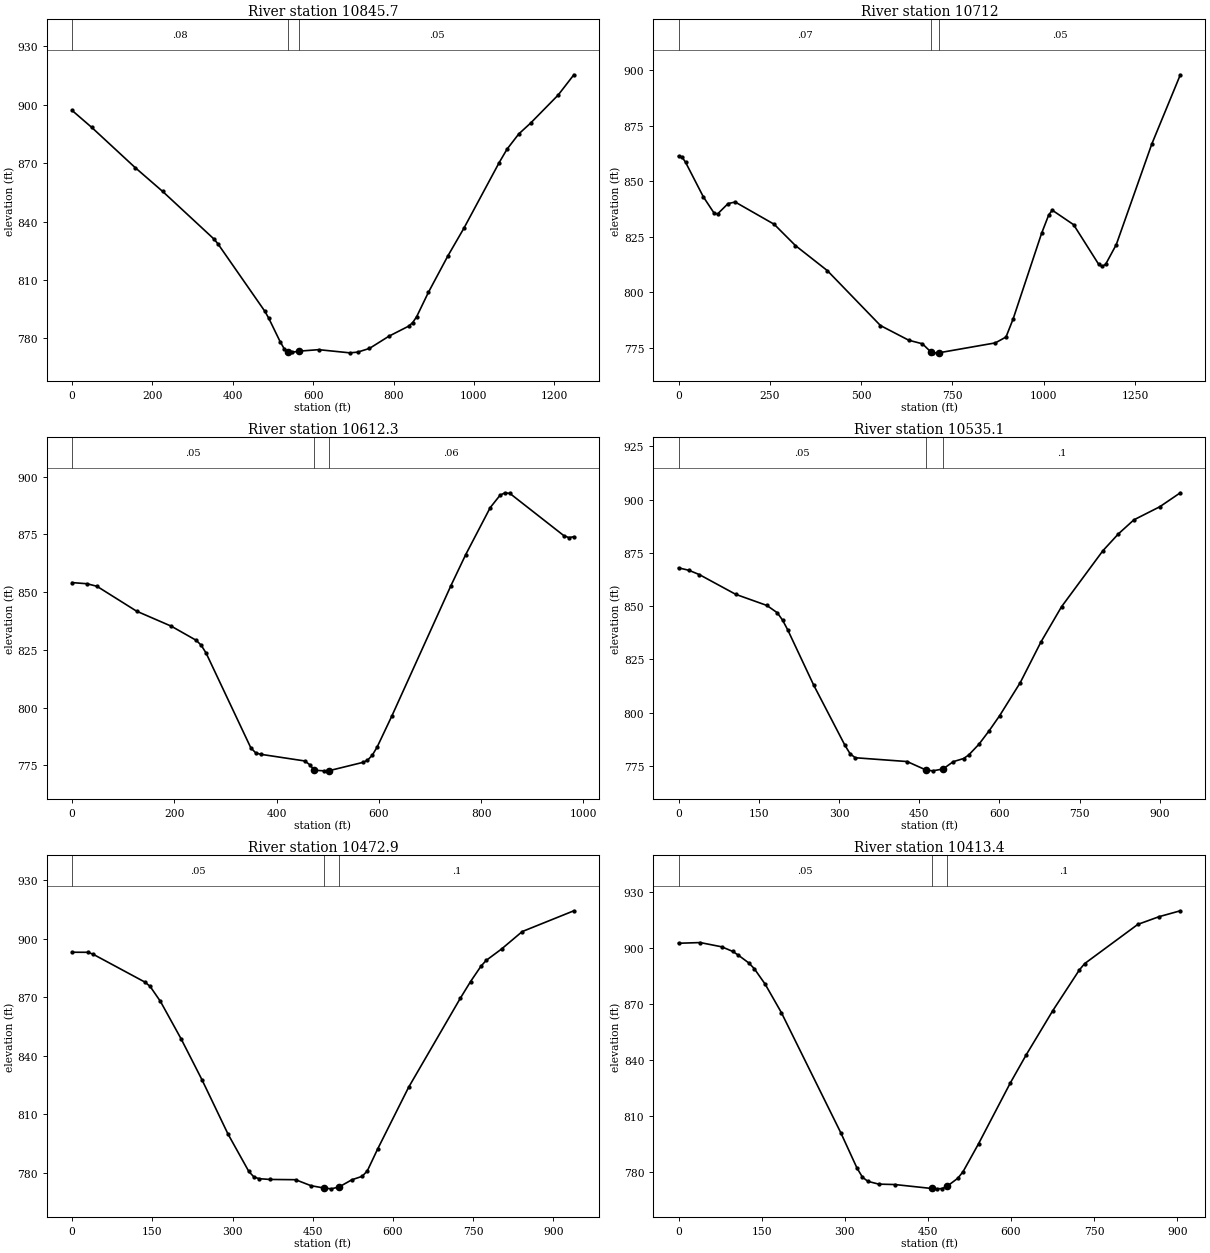
Type RM Length L Ch R = 1 ,10845.7 ,134.7,133.7,132.7
XS GIS Cut Line= 4
     1900467.111       627348.45      1900920.67       627267.72
     1901097.753       627227.79     1901688.031      627088.033
#Sta/Elev= 30
       0  897.07      49  888.34   156.8  867.75   225.4  855.48   352.9  831.07
   362.7  828.65   479.8  793.91   489.4  790.38     518  778.24   527.6   774.8
   537.1  773.14   546.7  772.85   565.8  773.46   613.6  774.21   691.1  772.58
   710.7  772.94   740.1  774.85     789  781.17   837.9  786.31   847.7  788.13
   857.5  791.11   886.8  803.65   935.7  822.52   974.9  836.49  1062.9  870.27
  1082.5  877.19  1111.8  885.02  1141.2  890.57  1209.7  904.97  1248.8  915.38
#Mann= 3 , 0 , 0
       0     .08       0   537.1    .045       0   565.8     .05       0
Bank Sta=537.1,565.8
XS Rating Curve= 0 ,0
Exp/Cntr=0.3,0.1

Type RM Length L Ch R = 1 ,10712   ,97.6,99.6,101.7
XS GIS Cut Line= 4
       1900418.5      627719.543     1900961.034      627398.363
     1901095.583       627361.47     1901688.031      627244.283
#Sta/Elev= 30
       0  861.27     9.7  860.82    19.4  858.43    67.9  842.92      97  835.67
   106.7  835.18   135.8  839.89   155.2  840.57   261.9  830.55   320.1  820.96
   407.4  809.68   552.9  784.93   630.5  778.31   667.7  776.72     692  772.86
   695.6  772.64   714.2   772.7   867.4  777.12   896.6  779.77   916.1   787.9
     994  826.45  1013.5  834.74  1023.2   836.9  1081.7  830.37  1149.9  812.64
  1159.6  811.58  1169.4  812.53  1198.6  821.42    1296  866.81  1373.9   897.9
#Mann= 3 , 0 , 0
       0     .07       0     692    .045       0   714.2     .05       0
Bank Sta=692,714.2
XS Rating Curve= 0 ,0
Exp/Cntr=0.3,0.1

Type RM Length L Ch R = 1 ,10612.3 ,58.6,77.2,93.3
XS GIS Cut Line= 4
     1900605.566      627643.588     1900982.302      627487.338
     1901168.066      627454.352     1901551.746      627424.838
#Sta/Elev= 30
       0   854.1    29.1  853.61    48.6  852.51   126.2  841.73   194.2  835.21
   242.8  829.11   252.5  826.99   262.2  823.55   349.6  782.55   359.3  780.34
     369  779.76     455  776.88   464.4  775.32   473.9  772.86   492.8   772.6
   502.2  772.64   568.2  776.23   577.7  777.17   587.1  779.38   596.5  782.85
   625.4  796.36   740.8  852.74   769.7  866.18   817.8  886.59     837  891.93
   846.6  892.99   856.3  892.69   962.1  874.36   971.7  873.59   981.3  873.97
#Mann= 3 , 0 , 0
       0     .05       0   473.9    .045       0   502.2     .06       0
Bank Sta=473.9,502.2
XS Rating Curve= 0 ,0
Exp/Cntr=0.3,0.1

Type RM Length L Ch R = 1 ,10535.1 ,64.6,62.2,61.6
XS GIS Cut Line= 4
     1900640.288      627657.477     1901034.385      627518.588
     1901164.593      627579.352     1901534.385      627650.533
#Sta/Elev= 30
       0  867.95    19.4   866.8    38.9  864.78   106.9  855.51   165.2  850.28
   184.6  846.86   194.4  843.43   204.1  838.84   252.7  812.85     311  784.64
   320.7  780.64   330.4  778.75   427.4  776.96  462.78  772.97   475.3   772.6
   494.5  773.47   513.6  776.91   532.8  778.37   542.4  780.01   561.5  785.06
   580.9   791.5   600.2  798.47   638.8  814.02   677.4  833.07     716  849.68
   793.3  875.98   822.2  883.88   851.2  890.48   899.5  896.62   938.1  903.21
#Mann= 3 , 0 , 0
       0     .05       0  462.78    .045       0   494.5      .1       0
Bank Sta=462.78,494.5
XS Rating Curve= 0 ,0
Exp/Cntr=0.3,0.1

Type RM Length L Ch R = 1 ,10472.9 ,66.2,59.5,53.2
XS GIS Cut Line= 4
     1900642.024      627713.033     1901036.121      627574.144
     1901166.329      627634.908     1901536.121      627706.088
#Sta/Elev= 30
       0  892.96    29.2  892.93    38.9     892     136  877.68   145.8  875.49
   165.2  867.76   204.1  848.43   242.9  827.58   291.5  799.78   330.4  780.62
   340.1  777.74   349.8   776.9   369.3  776.51   417.8  776.37   446.6  773.31
  470.83  772.11   484.8  771.69   499.8  772.75   523.2  776.35   542.4  778.11
     552  780.92   571.2  792.06   629.1   823.7   725.7  869.32     745  877.94
   764.3  885.75     774  888.74   802.9  894.61   841.6  903.56   938.1  914.21
#Mann= 3 , 0 , 0
       0     .05       0  470.83    .045       0   499.8      .1       0
Bank Sta=470.83,499.8
XS Rating Curve= 0 ,0
Exp/Cntr=0.3,0.1

Type RM Length L Ch R = 1 ,10413.4 ,232.6,228.2,224.4
XS GIS Cut Line= 4
     1900654.177      627751.227     1901051.746      627650.533
     1901188.899      627681.783     1901539.593      627735.602
#Sta/Elev= 30
       0  902.65    39.1  903.02    78.1  900.73    97.6   898.3   107.4  896.37
   126.9  892.07   136.7  889.02   156.2  880.77   185.5  865.51   292.9  800.97
   322.2  781.99     332  777.16   341.8  774.94   361.3  773.46   390.6  773.23
     457  771.12   466.4  770.93   475.8   771.1   485.2  772.43   503.9  776.58
   513.3  780.04   541.4  795.09   598.7  827.69   627.5  842.82   675.4  866.49
   723.4  888.35     733  891.75   828.9  912.77   867.2   916.9   905.6  920.07
#Mann= 3 , 0 , 0
       0     .05       0     457    .045       0   485.2      .1       0
Bank Sta=457,485.2
XS Rating Curve= 0 ,0
Exp/Cntr=0.3,0.1

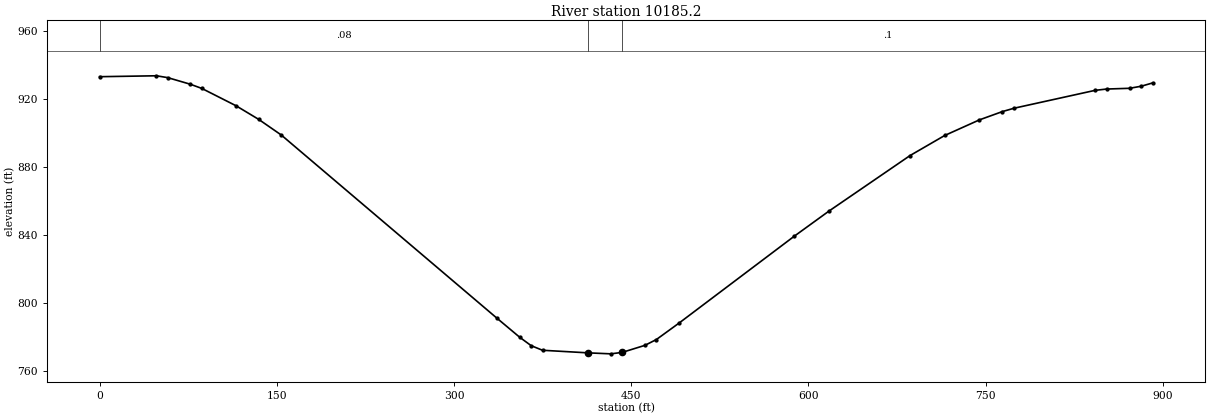
Type RM Length L Ch R = 1 ,10185.2 ,400.2,393.1,385
XS GIS Cut Line= 4
     1900673.274       627888.38     1901067.371      627886.644
     1901173.225      627894.075     1901562.506      627933.606
#Sta/Elev= 30
       0  932.96    48.1   933.5    57.7   932.4    76.9  928.51    86.5  926.07
   115.4  915.92   134.6  907.92   153.8   898.7   336.4  791.11   355.6  779.96
   365.3  775.02   374.9  772.32   413.4   770.8   432.7  770.22   442.3  771.06
   461.6  775.21   471.3  778.62   490.6  788.34   588.2  839.38   617.6  854.15
   686.1  886.68   715.4  898.45   744.8  907.62   764.3   912.5   774.1  914.45
   842.6  924.93   852.4  925.71   871.9  926.15   881.7  927.36   891.5  929.32
#Mann= 3 , 0 , 0
       0     .08       0   413.4    .045       0   442.3      .1       0
Bank Sta=413.4,442.3
XS Rating Curve= 0 ,0
Exp/Cntr=0.3,0.1