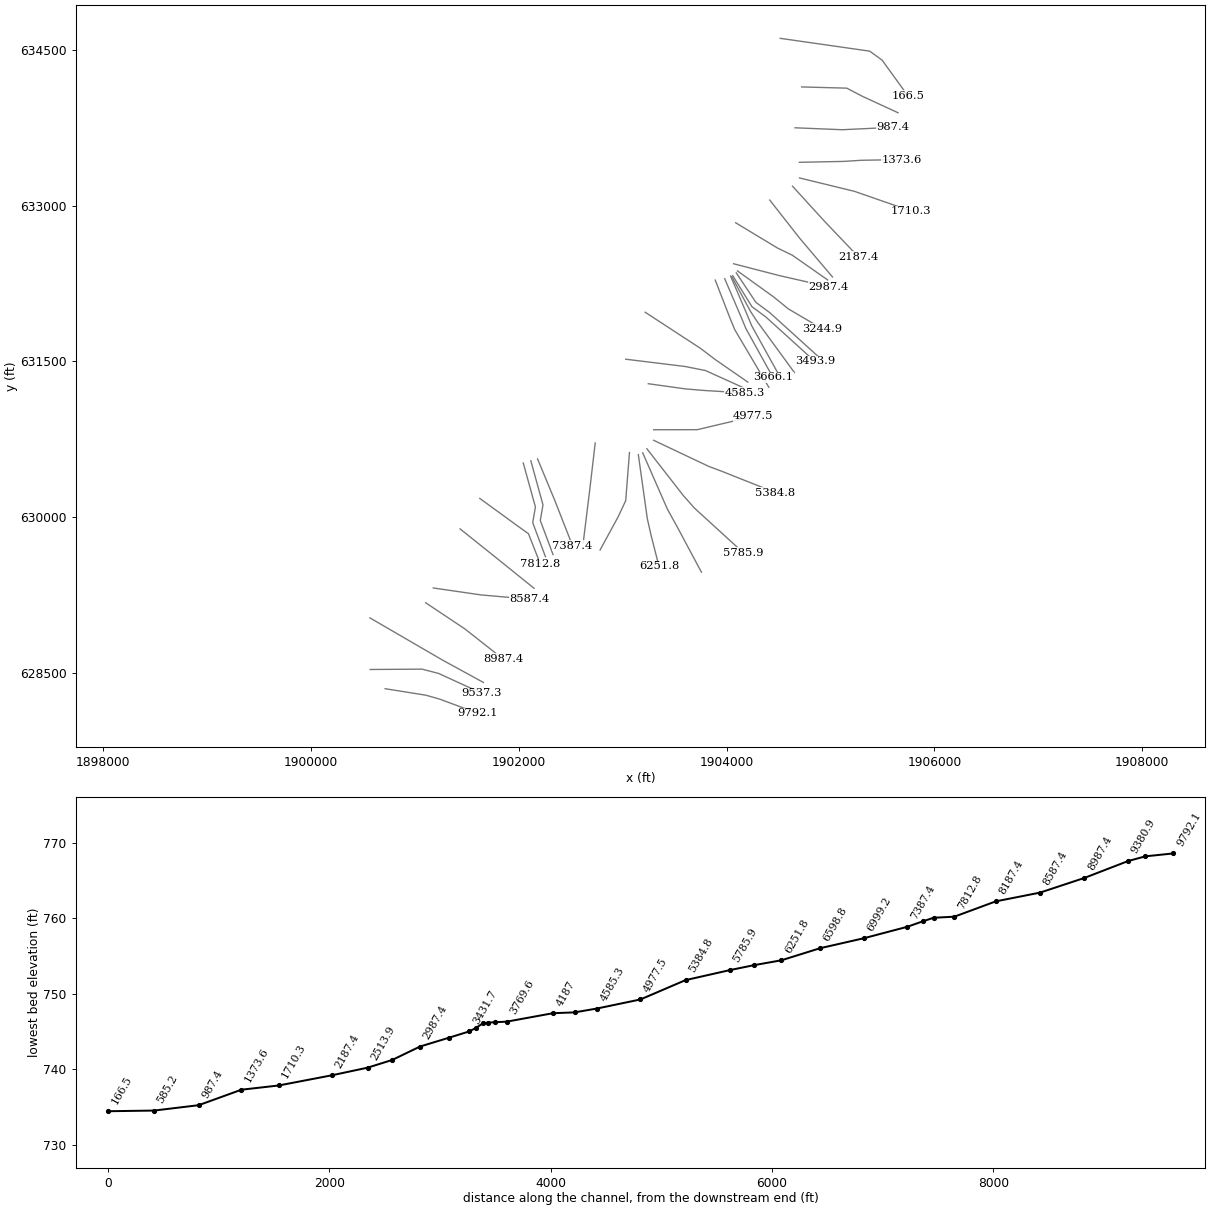
HEC-RAS study RushRun.prj: RushRun

--- RushRun.g01 (geometry) --- (continued)

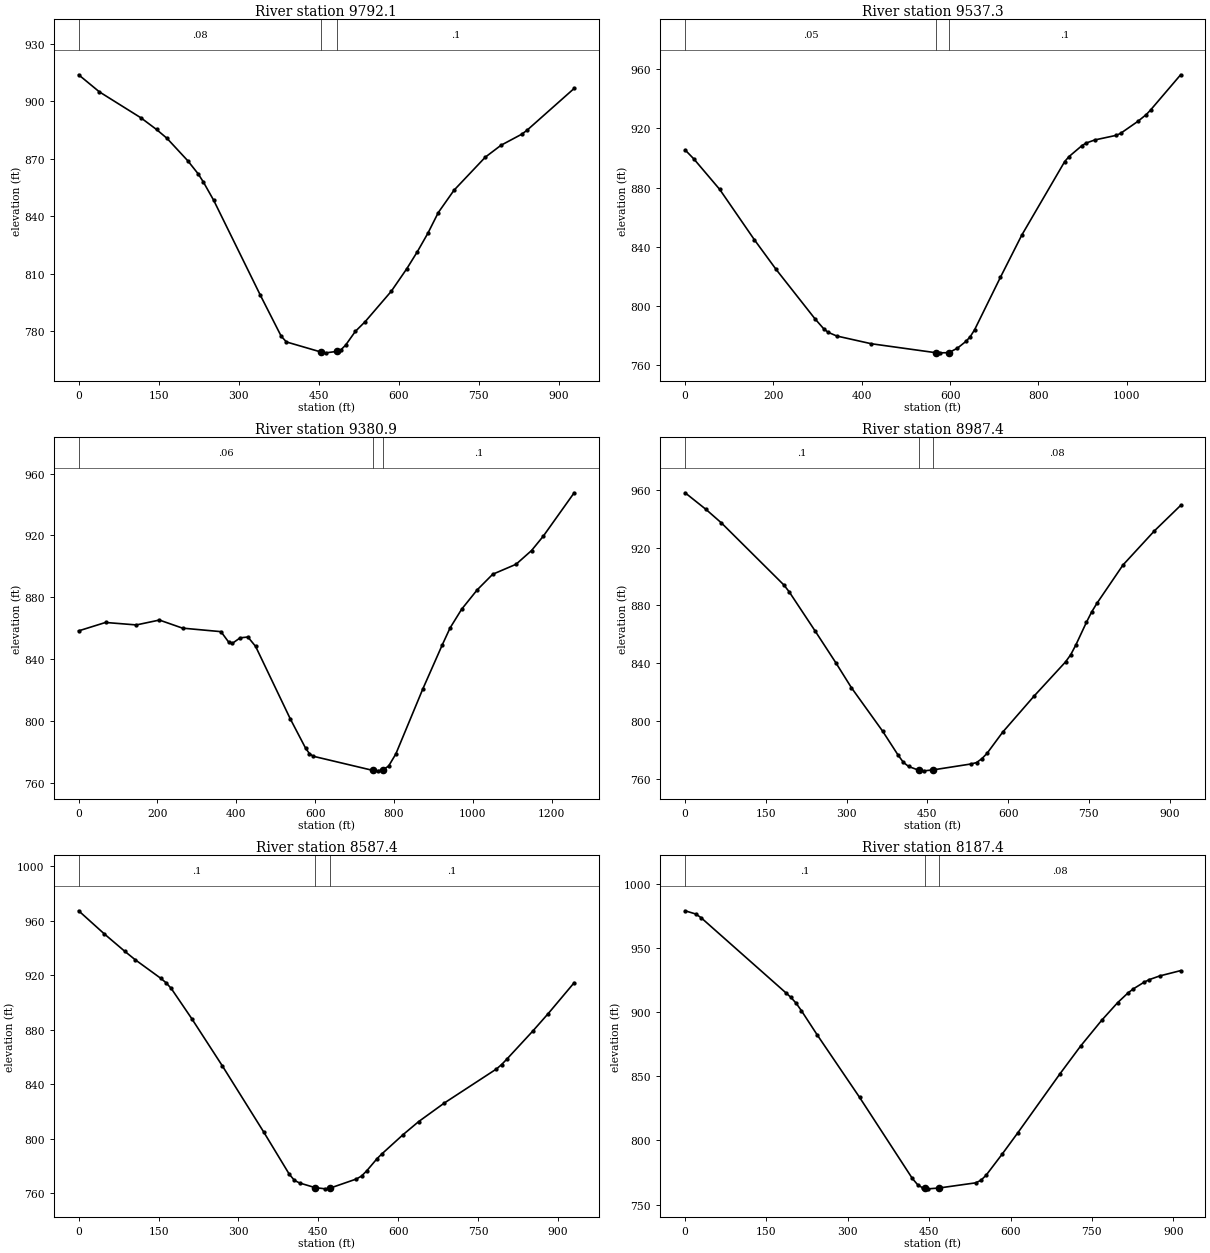
Type RM Length L Ch R = 1 ,9792.1  ,254.2,254.8,254.5
XS GIS Cut Line= 4
     1900713.221      628343.842     1901107.302      628280.741
     1901239.817      628242.902     1901606.654      628105.757
#Sta/Elev= 30
       0  913.92    38.9  904.99   116.8  891.41     146  885.32   165.5  880.73
   204.4  869.02   223.9  862.18   233.6  857.94   253.1  848.31   340.7  798.61
   379.6  777.28   389.4  774.28   454.2  769.01   463.4  768.59   484.9  769.38
     491  770.05   500.2  772.57   518.5  779.79   536.9  784.87   585.9  800.78
   615.2  812.67   634.8  821.48   654.4  831.07     674  841.92   703.4  853.57
   762.1  870.87   791.5  877.08   830.6   882.9   840.4  884.97   928.6  906.79
#Mann= 3 , 0 , 0
       0     .08       0   454.2    .045       0   484.9      .1       0
Bank Sta=454.2,484.9
XS Rating Curve= 0 ,0
Exp/Cntr=0.3,0.1

Type RM Length L Ch R = 1 ,9537.3  ,162.4,156.4,150.6
XS GIS Cut Line= 4
     1900569.107      628529.005     1901069.107      628532.477
     1901228.829      628490.811      1901643.76      628299.838
#Sta/Elev= 30
       0  905.48    19.6  899.47    78.4  878.75   156.9  844.69   205.9  824.68
   294.1  791.19   313.7  784.52   323.5  782.14   343.2   779.6   421.6  774.35
     568  768.27   577.7   768.2   597.1  768.32   616.5  771.37     636     776
   645.7  779.22   655.4  783.83   713.7  819.24   762.3  847.92   859.4  897.65
   869.2  901.01   898.3  908.38     908  910.15   927.5  912.24   976.1  915.36
   985.8  916.68  1024.7  924.75  1044.1  929.43  1053.8  932.52  1121.8  956.33
#Mann= 3 , 0 , 0
       0     .05       0     568    .045       0   597.1      .1       0
Bank Sta=568,597.1
XS Rating Curve= 0 ,0
Exp/Cntr=0.3,0.1

Type RM Length L Ch R = 1 ,9380.9  ,395.1,393.5,389.9
XS GIS Cut Line= 4
     1900566.937      629026.835     1901182.588      628668.464
      1901262.25      628621.887     1901658.971      628404.353
#Sta/Elev= 30
       0  858.16    68.3   863.6   146.4     862   204.9  865.16   263.5  859.93
   361.1  857.65   380.6  850.89   390.3  850.15   409.8  853.65   429.4  854.18
   448.9  848.14   536.7  801.32   575.7  782.26   585.5  778.72   595.3     777
  745.77  767.89   758.5  767.57     771  768.19   786.2  770.59   804.6  778.45
   873.5  820.79   922.7  849.22   942.3  860.05   971.8  872.23  1011.2  884.73
  1050.5  894.81  1109.6  901.25  1148.9  910.13  1178.4  919.33  1257.1  947.53
#Mann= 3 , 0 , 0
       0     .06       0  745.77    .045       0     771      .1       0
Bank Sta=745.77,771
XS Rating Curve= 0 ,0
Exp/Cntr=0.3,0.1

Type RM Length L Ch R = 1 ,8987.4  ,390.6,400,412.8
XS GIS Cut Line= 3
     1901103.469      629172.838     1901480.851      628920.646
      1901847.21       628631.59
#Sta/Elev= 30
       0  958.13    38.6  946.67    67.6  937.19   183.5  894.22   193.2  889.56
   241.4   862.4   280.1  840.24     309  822.98     367  792.83     396  776.08
   405.6  771.19   415.3  768.36   434.6   765.7   444.2  765.34   461.4  766.04
   531.7  770.13   541.4  771.08   551.1  773.68   560.8   777.4     590  792.16
   648.3  817.16   706.7  840.84   716.4  845.86   726.1  852.76   745.6  868.34
   755.3  875.51     765  881.46   813.6  908.11   871.9  931.73   920.6  949.37
#Mann= 3 , 0 , 0
       0      .1       0   434.6    .045       0   461.4     .08       0
Bank Sta=434.6,461.4
XS Rating Curve= 0 ,0
Exp/Cntr=0.3,0.1

Type RM Length L Ch R = 1 ,8587.4  ,411.2,400,386.7
XS GIS Cut Line= 3
     1901176.958      629315.385     1901634.979      629248.615
     1902100.366      629207.302
#Sta/Elev= 30
       0  967.22    48.2  950.27    86.8  937.45   106.1  931.36   154.3  917.68
   163.9  914.53   173.6  910.39   212.2  888.22     270  853.38   347.2  805.17
   395.4   774.1     405  769.64   414.6  767.71   443.6  764.31   462.9   763.4
   472.6  764.02   521.3  770.61     531  772.78   540.7  776.58   560.2  785.57
   569.9  789.27   608.9   803.1   638.1  812.66   686.7  826.39   784.1  851.23
   793.8  854.47   803.5  858.38   852.2  878.95   881.4  891.87   930.1  914.49
#Mann= 3 , 0 , 0
       0      .1       0   443.6    .045       0   472.6      .1       0
Bank Sta=443.6,472.6
XS Rating Curve= 0 ,0
Exp/Cntr=0.3,0.1

Type RM Length L Ch R = 1 ,8187.4  ,373.2,374.6,375.8
XS GIS Cut Line= 3
     1901434.662      629885.513     1901791.975      629598.994
     1902146.549      629312.687
#Sta/Elev= 30
       0  978.84    19.5  976.35    29.2  973.55   185.2  915.18   194.9  911.46
   204.6  906.91   214.4  901.06   243.6  882.15   321.6  833.58     419  770.33
   428.8  765.45   438.5  762.83  443.22  762.55   448.3  762.24   467.7  762.86
   535.6   766.9   545.3  768.83     555  772.83   584.1  788.99   613.2  805.74
   690.7  851.55   729.5  873.59   768.3  893.62   797.4  907.22   816.8  914.91
   826.5     918   845.9   923.1   855.6  925.17     875  928.07   913.7  932.23
#Mann= 3 , 0 , 0
       0      .1       0  443.22    .045       0   467.7     .08       0
Bank Sta=443.22,467.7
XS Rating Curve= 0 ,0
Exp/Cntr=0.3,0.1

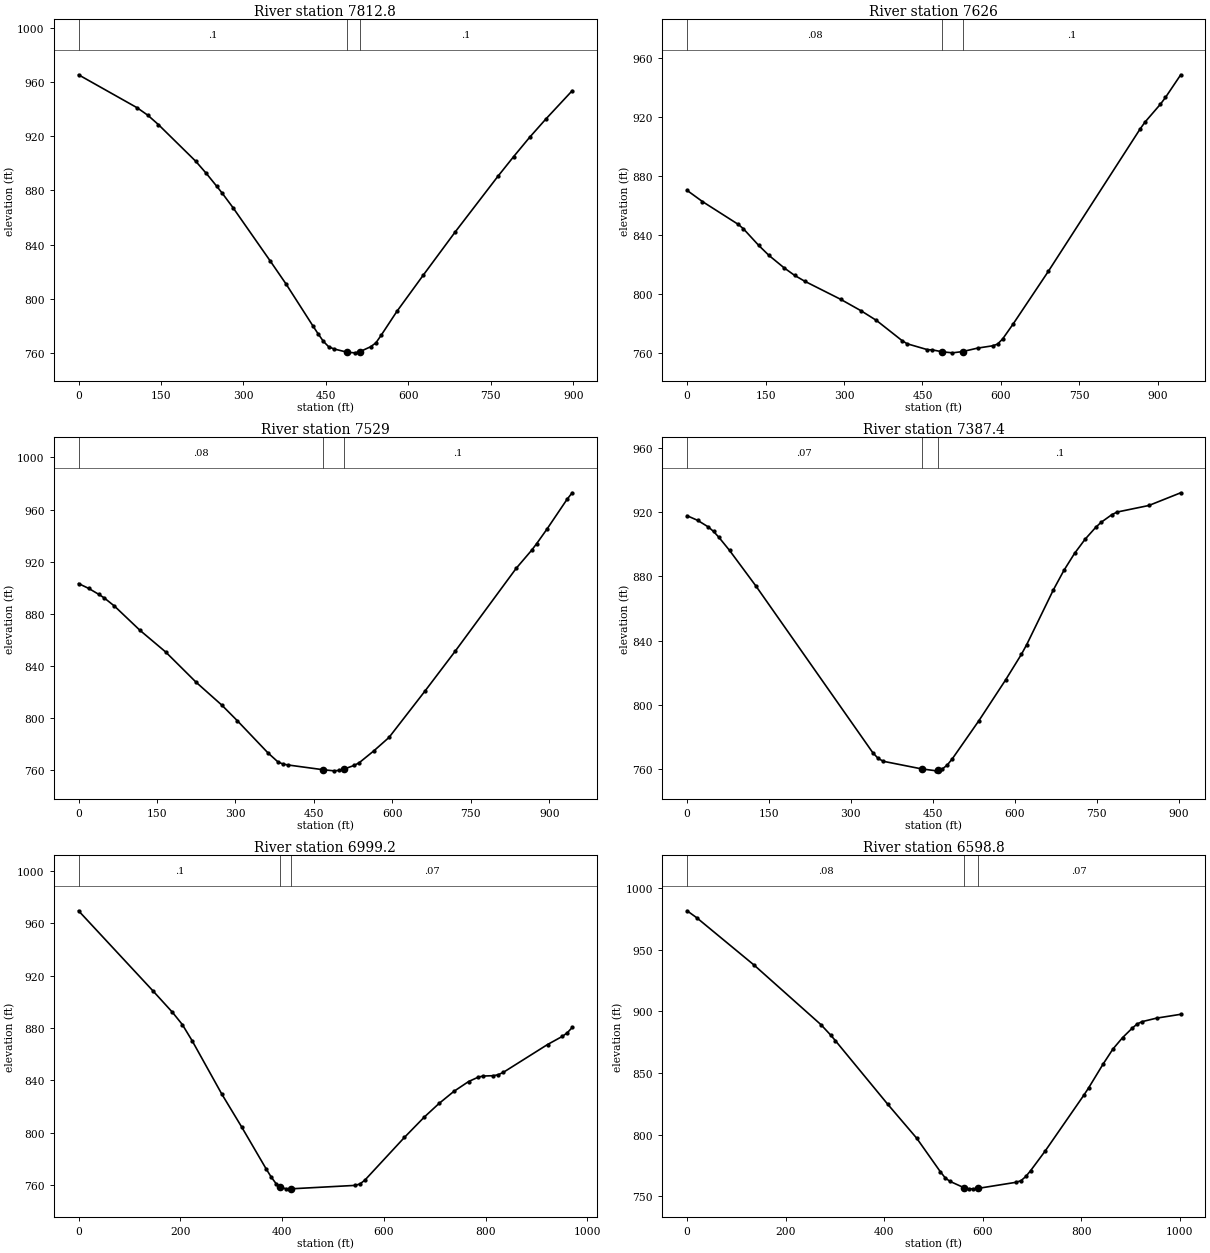
Type RM Length L Ch R = 1 ,7812.8  ,221.6,186.8,151.2
XS GIS Cut Line= 4
     1901624.771      630178.957     1901992.425      629910.852
     1902093.219      629838.861     1902209.588      629541.881
#Sta/Elev= 30
       0  965.24   106.5  940.94   125.9  935.45   145.2  928.54     213  901.55
   232.4  892.52   251.7  882.88   261.4   877.9   280.8  867.35   348.5  828.04
   377.6  810.88     426  780.25   435.7  774.27   445.4  768.66     455  764.68
   464.6  763.08  489.17  760.61   502.7  760.21   512.2  761.16   531.2  764.69
   540.8  767.53   550.3  773.08   578.9   790.7   627.2   817.6   685.2   849.4
   762.5  890.24   791.5  904.95   820.5  919.14   849.5  932.39   897.9  953.48
#Mann= 3 , 0 , 0
       0      .1       0  489.17    .045       0   512.2      .1       0
Bank Sta=489.17,512.2
XS Rating Curve= 0 ,0
Exp/Cntr=0.3,0.1

Type RM Length L Ch R = 1 ,7626    ,89.7,97,103.8
XS GIS Cut Line= 4
     1902042.921      630521.048     1902160.108      630096.569
     1902134.067      629945.527     1902256.463      629617.402
#Sta/Elev= 30
       0  870.18    29.4  862.61    97.9  847.13   107.6  844.19     137  832.88
   156.6  826.09   185.9  817.57   205.5   812.6   225.1  808.57   293.6  796.35
   332.7  788.57   362.1  782.03     411  768.36   420.8  766.21   459.5  762.22
   469.1  762.06   488.3  760.75   507.4  760.07   526.6  760.91   555.3  763.27
     584  764.83   593.6  765.99   603.4  769.54   622.8  779.32   690.9  815.44
     866  911.74   875.7  916.56   904.9  928.57   914.6  933.16   943.8  948.54
#Mann= 3 , 0 , 0
       0     .08       0   488.3    .045       0   526.6      .1       0
Bank Sta=488.3,526.6
XS Rating Curve= 0 ,0
Exp/Cntr=0.3,0.1

Type RM Length L Ch R = 1 ,7529    ,126.4,141.6,156.9
XS GIS Cut Line= 4
     1902115.838      630541.881     1902233.025      630117.402
     1902206.983       629966.36     1902329.379      629638.235
#Sta/Elev= 30
       0  903.26    19.6   899.5    39.1  894.88    48.9   892.3    68.5  886.04
   117.4   867.4   166.4  850.84   225.1  827.44     274  809.98   303.4  798.12
   362.1  773.39   381.6  766.33   391.4  764.76   401.2  764.06   467.7  760.45
   488.3   759.6   497.8  759.92   507.4  760.94   526.6  763.71   536.2  765.69
   564.9  775.04   593.6  785.23   661.7  820.46   720.1  851.36   836.8  914.98
     866  928.68   875.7  933.79   895.2  944.81   934.1  967.96   943.8  972.89
#Mann= 3 , 0 , 0
       0     .08       0   467.7    .045       0   507.4      .1       0
Bank Sta=467.7,507.4
XS Rating Curve= 0 ,0
Exp/Cntr=0.3,0.1

Type RM Length L Ch R = 1 ,7387.4  ,399.9,388.1,377.4
XS GIS Cut Line= 3
     1902180.942       630560.11     1902347.985      630156.071
     1902517.841      629721.531
#Sta/Elev= 30
       0  917.79    19.4   914.9    38.9  910.79    48.6  907.96    58.3  904.32
    77.7   896.2   126.3  873.88     340  770.19   349.8  766.61   359.5   764.8
   429.7  760.06   456.6  758.87  460.16  759.22   466.4   759.8   476.1  762.39
   485.8  766.47   534.4  790.18     583  815.42   612.2   831.5   621.9  837.56
   670.5  871.53   689.9  883.72   709.4  894.32   728.8  903.18   748.2  910.56
     758  913.67   777.4  918.38   787.1  920.06   845.4  924.16   903.8  932.08
#Mann= 3 , 0 , 0
       0     .07       0   429.7    .045       0  460.16      .1       0
Bank Sta=429.7,460.16
XS Rating Curve= 0 ,0
Exp/Cntr=0.3,0.1

Type RM Length L Ch R = 1 ,6999.2  ,406.3,400.5,392.7
XS GIS Cut Line= 3
     1902735.629      630713.756      1902686.15      630289.277
     1902620.006      629750.232
#Sta/Elev= 30
       0  969.41   145.7  908.58   184.5  892.05     204  882.66   223.4  870.26
   281.7  829.57   320.5  804.66   369.1  772.38   378.8  766.34   388.5  761.23
   396.4  758.83   407.9  757.37   417.6  757.38   543.7     760   553.4  761.13
   563.1  764.11   640.7  796.62   679.5  812.04   708.6  822.45   737.7  831.66
   766.8   839.2   786.2  842.63   795.9   843.4   815.3  843.65     825  844.38
   834.7  846.13     922  867.43     951  873.62   960.7  876.36   970.4  880.42
#Mann= 3 , 0 , 0
       0      .1       0   396.4    .045       0   417.6     .07       0
Bank Sta=396.4,417.6
XS Rating Curve= 0 ,0
Exp/Cntr=0.3,0.1

Type RM Length L Ch R = 1 ,6598.8  ,332.8,347,361.9
XS GIS Cut Line= 4
     1903065.378      630621.748     1903029.032      630157.333
     1902956.115      630001.083     1902782.504      629681.638
#Sta/Elev= 30
       0  981.45    19.4  975.87   135.9  937.46   271.7  889.12   291.2  880.77
   300.8  876.24   407.6  824.42   465.8  797.18   513.7  770.06   523.3   765.2
   532.9   762.2   561.6  757.01   571.2   756.1   580.8  756.03   590.4  756.39
   667.7  761.34   677.6  762.64   687.4  766.04   697.2  770.79   726.7  786.69
   805.3  832.03   815.1  838.02   844.6   857.4   864.3  869.42   883.9  878.67
   903.6  886.39   913.4  889.68   923.2  891.56   952.7  894.41  1001.8  897.53
#Mann= 3 , 0 , 0
       0     .08       0   561.6    .045       0   590.4     .07       0
Bank Sta=561.6,590.4
XS Rating Curve= 0 ,0
Exp/Cntr=0.3,0.1

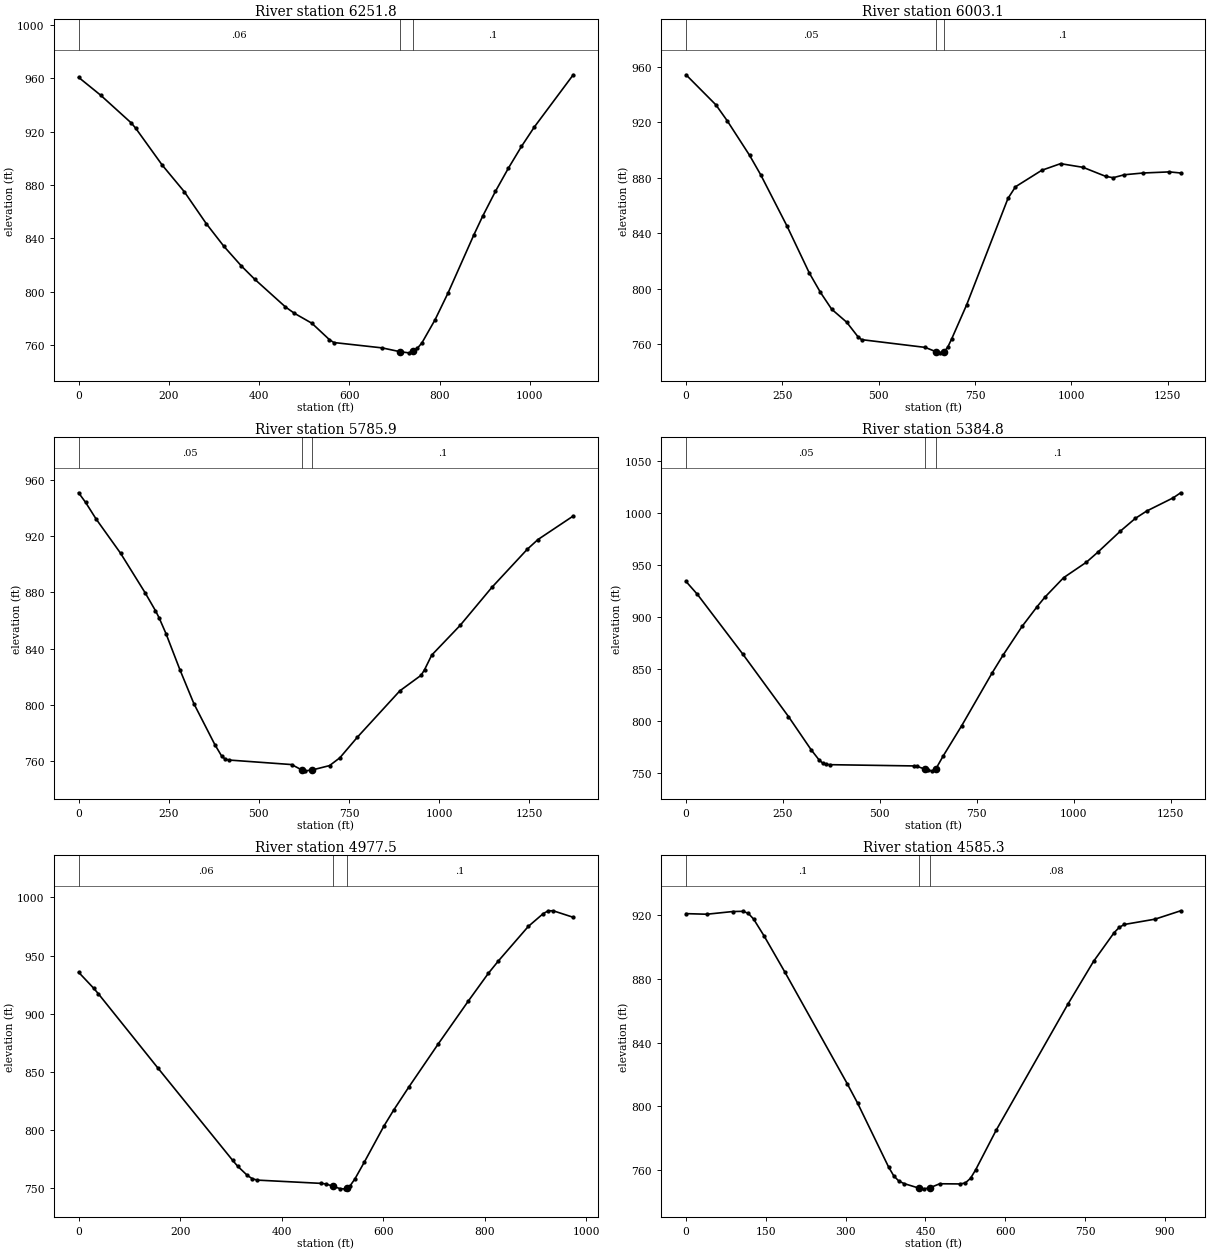
Type RM Length L Ch R = 1 ,6251.8  ,242.2,248.6,254.9
XS GIS Cut Line= 4
      1903150.71      630600.979     1903237.365      629982.853
     1903273.824      629821.395     1903349.344       629524.52
#Sta/Elev= 30
       0  960.56    48.8  947.21     117  926.34   126.8  922.35   185.3   894.9
   234.1  875.04   282.8  851.15   321.8   834.2   360.8  819.38   390.1  809.54
   458.4  788.76   477.9  784.08   516.9  776.57   555.9  764.26   565.6  762.15
   672.8  758.13   711.8  755.32   731.3  754.44     741  755.64   750.8  757.95
   760.5  761.77   789.7  779.11   818.4  799.09   875.8   842.7     895  856.46
   923.7  875.32   952.4  892.66   981.2  908.82  1009.9  923.46    1096  962.47
#Mann= 3 , 0 , 0
       0     .06       0   711.8    .045       0     741      .1       0
Bank Sta=711.8,741
XS Rating Curve= 0 ,0
Exp/Cntr=0.3,0.1

Type RM Length L Ch R = 1 ,6003.1  ,212.2,217.2,222.3
XS GIS Cut Line= 4
     1903193.094       630618.27     1903430.074      630076.603
     1903529.032      629896.916     1903758.199      629467.228
#Sta/Elev= 30
       0  954.14    77.5  932.48   106.6  921.13   164.8  896.14   193.8  882.06
   261.7   845.3   319.8  811.36   348.9  797.29     378  785.19   416.8  775.88
   445.8   765.5   455.5   763.3   620.5  757.71   649.8  754.45   659.6  753.79
   670.3  754.72   679.2  757.98   688.9  763.62     728  788.32   835.3  865.06
   854.8  873.45     923  885.33   971.7   890.1  1030.1  887.45  1088.6  880.98
    1108  879.97  1137.3  882.11    1186  883.37  1254.1  884.17  1283.4  883.37
#Mann= 3 , 0 , 0
       0     .05       0   649.8    .045       0   670.3      .1       0
Bank Sta=649.8,670.3
XS Rating Curve= 0 ,0
Exp/Cntr=0.3,0.1

Type RM Length L Ch R = 1 ,5785.9  ,390.2,401.1,412.1
XS GIS Cut Line= 4
      1903232.82      630658.418     1903583.719      630206.812
     1903691.261      630085.349     1904161.844      629654.728
#Sta/Elev= 30
       0  950.88    19.4  944.06    48.5  932.26   116.3  907.93   184.2  879.92
   213.2  867.06     223  862.15   242.3   850.8   281.1     825   319.9  800.86
     378  771.75   397.4   763.4   407.1  761.45   416.8  760.83     591   757.6
   619.6  753.69   629.2  753.14   648.2  753.77     696  756.86   724.6   762.4
   773.4  777.11   891.2  810.07     950   821.1   959.8  825.19   979.5  835.46
    1058   856.5  1146.3  883.61  1244.4  910.69  1273.9  917.58    1372  934.37
#Mann= 3 , 0 , 0
       0     .05       0   619.6    .045       0   648.2      .1       0
Bank Sta=619.6,648.2
XS Rating Curve= 0 ,0
Exp/Cntr=0.3,0.1

Type RM Length L Ch R = 1 ,5384.8  ,393.9,407.3,420.4
XS GIS Cut Line= 4
     1903298.008      630739.828     1903828.511      630488.062
     1903953.491      630441.128     1904469.136      630235.458
#Sta/Elev= 30
       0  934.28    29.4  921.84   146.8  864.12   264.2  804.15     323  771.96
   342.5  762.68   352.3   759.3   362.1  758.02   371.9  757.74   587.2  756.54
   596.8  756.02   615.8   753.5   625.4  752.16   634.9  751.81   644.4  753.68
   663.5  766.26   711.2  795.38   788.9  845.75   818.1  863.49   866.8  890.98
   905.8  910.11   925.2  918.94   973.9  937.92  1032.4  952.75  1061.6  962.28
    1120  982.68    1159   995.1  1188.2 1002.14  1256.4 1014.83  1275.9 1019.74
#Mann= 3 , 0 , 0
       0     .05       0   615.8    .045       0   644.4      .1       0
Bank Sta=615.8,644.4
XS Rating Curve= 0 ,0
Exp/Cntr=0.3,0.1

Type RM Length L Ch R = 1 ,4977.5  ,399.2,392.2,385.3
XS GIS Cut Line= 4
     1903298.451      630841.587     1903719.136      630842.228
     1903904.032      630886.499     1904258.199      630969.833
#Sta/Elev= 30
       0   935.6    29.4  921.99    39.1  917.01   156.5  853.06   303.3  773.89
   313.1  768.86   332.6  760.75   342.4  757.93   352.2  756.76   477.7  753.95
   487.2  753.48   501.6  751.43   515.8  749.32   525.2  749.25  529.07  750.31
   534.8  751.79   544.3   757.7   563.3  772.51   601.3  803.05   620.6  816.87
   650.1  836.47   709.1  874.25   768.1  910.97   807.5  934.77   827.1  945.32
   886.1  975.05   915.6  986.09   925.5  988.48   935.3  988.45   974.6  982.87
#Mann= 3 , 0 , 0
       0     .06       0   501.6    .045       0  529.07      .1       0
Bank Sta=501.6,529.07
XS Rating Curve= 0 ,0
Exp/Cntr=0.3,0.1

Type RM Length L Ch R = 1 ,4585.3  ,205.5,202.9,200.3
XS GIS Cut Line= 4
     1903246.535      631285.451     1903604.553      631235.458
     1903786.713      631220.271     1904171.423      631196.831
#Sta/Elev= 30
       0  921.14    39.1  920.77    87.9  922.47   107.5   922.6   117.2  921.25
     127  917.74   146.6  907.19   185.6  884.49   302.9  814.23   322.4  802.01
   380.7   761.8   390.4  756.22     400  752.95   409.6  751.38   438.5  748.42
   448.1  748.05     459  748.82   476.9  751.24   515.4  751.13     525  751.76
   534.7  754.69   544.3  759.98   582.8  784.86   717.7   864.2   765.9   891.1
   804.4  909.08   814.1  912.47   823.7  914.32   881.5  917.67   929.7  922.94
#Mann= 3 , 0 , 0
       0      .1       0   438.5    .045       0     459     .08       0
Bank Sta=438.5,459
XS Rating Curve= 0 ,0
Exp/Cntr=0.3,0.1

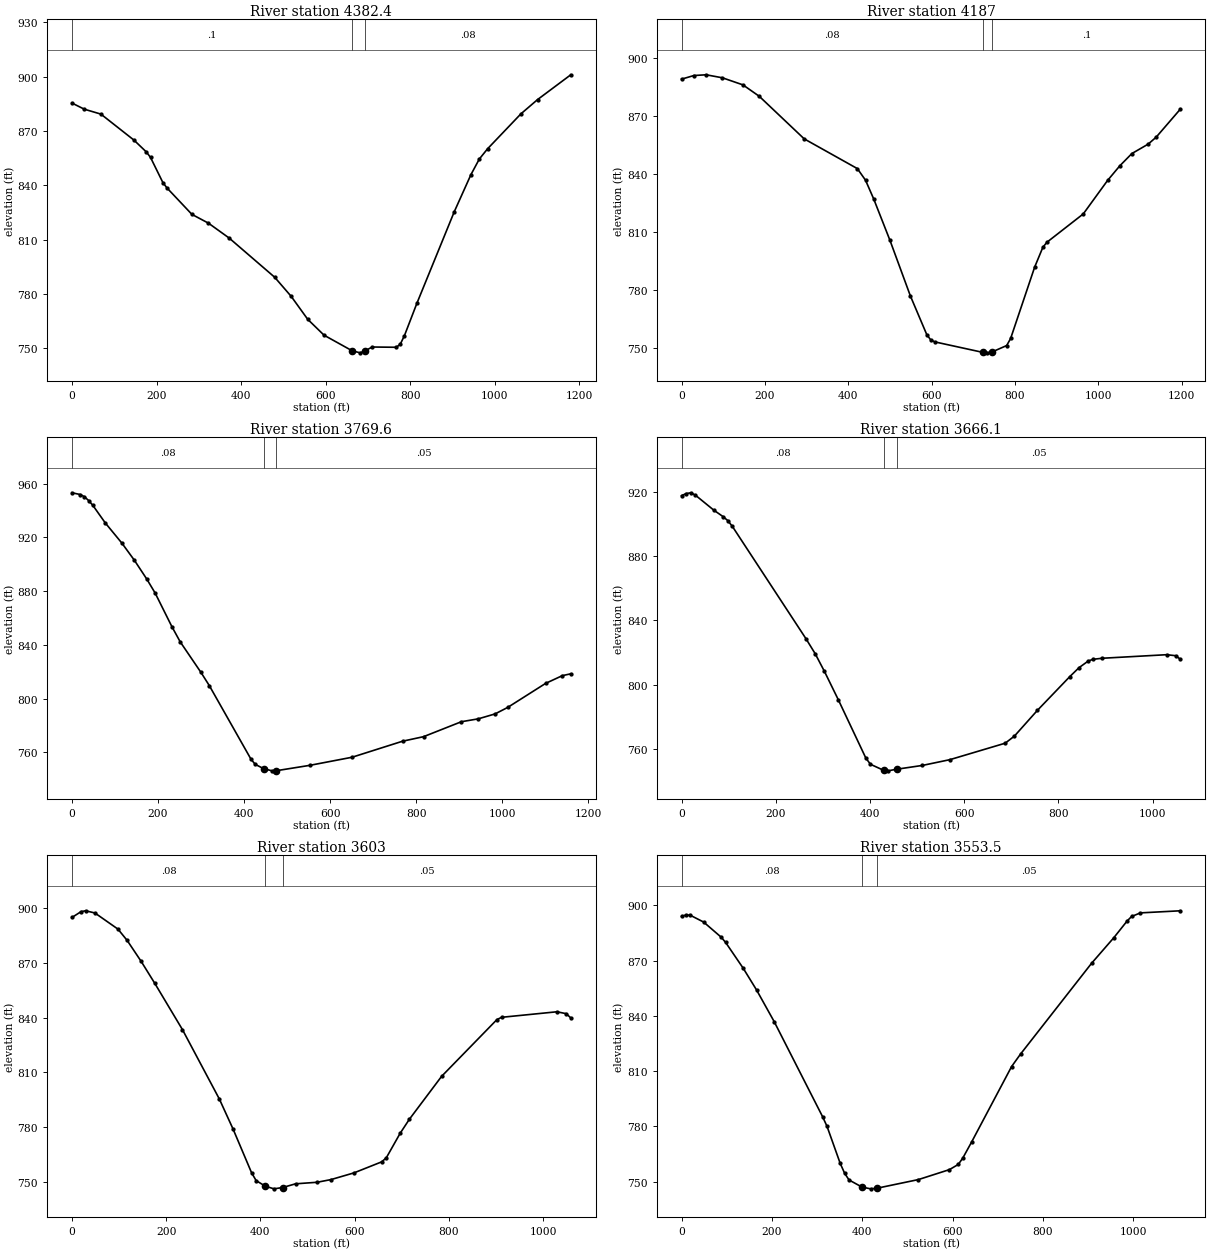
Type RM Length L Ch R = 1 ,4382.4  ,205.3,195.4,184.9
XS GIS Cut Line= 4
     1903029.032      631521.916     1903601.949      631451.603
     1903797.261      631412.541     1904164.449      631245.874
#Sta/Elev= 30
       0  885.44    29.4  882.03    68.5  879.33   146.8  864.95   176.1  858.41
   185.9  855.39   215.2  841.47     225  838.51   283.7  823.98   322.8  819.13
   371.8  810.91   479.4  789.28   518.5  778.71   557.6  766.04   596.2  757.28
   662.6  748.68   681.6  747.54   693.3  748.67     710  750.76   766.9  750.61
   776.4  752.29   786.2     757   815.7  774.88   904.2   825.5   943.6  845.96
   963.3  854.52   982.9   860.2  1061.6  879.45    1101  887.34  1179.6  901.04
#Mann= 3 , 0 , 0
       0      .1       0   662.6    .045       0   693.3     .08       0
Bank Sta=662.6,693.3
XS Rating Curve= 0 ,0
Exp/Cntr=0.3,0.1

Type RM Length L Ch R = 1 ,4187    ,429.4,417.3,405.3
XS GIS Cut Line= 4
     1903216.532      631975.041     1903749.716      631626.003
     1903893.615      631516.708     1904205.103      631300.918
#Sta/Elev= 30
       0  889.17    29.4  891.03    58.8  891.42      98  889.85   147.1   886.2
   186.3  880.28   294.1  858.24   421.6  842.84   441.2  836.85   460.8  827.16
     500  805.62     549  776.83   588.2  756.87     598  754.04   607.9  753.08
   722.9  747.66   732.4  747.43  745.24  747.93   779.9   751.2   789.4  754.86
   847.1  791.85   866.6  802.02   876.3  804.67   963.7  819.37    1022   836.7
  1051.2  844.24  1080.3  850.63  1119.2  855.48  1138.6  859.11  1196.9  873.71
#Mann= 3 , 0 , 0
       0     .08       0   722.9    .045       0  745.24      .1       0
Bank Sta=722.9,745.24
XS Rating Curve= 0 ,0
Exp/Cntr=0.3,0.1

Type RM Length L Ch R = 1 ,3769.6  ,103.5,103.5,103.4
XS GIS Cut Line= 4
     1903891.011      632284.937      1904034.24      631915.145
     1904078.842      631806.604     1904406.636      631251.083
#Sta/Elev= 30
       0  953.25    19.3  951.96      29  950.33    38.7   947.5    48.4  943.98
    77.4  930.85   116.1  915.77   145.1  903.03   174.1  888.93   193.4  878.58
   232.1   853.7   251.5  842.34   299.8  819.56   319.2  809.72   416.1  754.91
   425.9  751.13   445.5  747.92     465  746.31   474.8   746.4     553  750.42
   650.7  756.42     768  768.35   816.9  771.74   904.8  782.87   943.9     785
     983  788.67  1012.3   793.5  1100.3  811.37  1139.4  817.18  1158.9  818.51
#Mann= 3 , 0 , 0
       0     .08       0   445.5    .045       0   474.8     .05       0
Bank Sta=445.5,474.8
XS Rating Curve= 0 ,0
Exp/Cntr=0.3,0.1

Type RM Length L Ch R = 1 ,3666.1  ,63.1,63.2,63.1
XS GIS Cut Line= 4
     1903982.157      632297.958     1904143.615      631920.353
     1904185.282      631818.791     1904445.699      631347.437
#Sta/Elev= 30
       0  917.79     9.8  919.08    19.6  919.56    29.3  918.07    68.4  908.71
      88  904.71    97.8  902.27   107.6  898.67     264  828.59   283.6  819.23
   303.1  808.28   332.4   790.7   391.1   754.2   400.9  750.32     429  746.56
   438.1  746.24   456.4  747.24   511.3  749.62   569.4   753.2   686.9  763.47
   706.5   767.9   755.4  783.98     824  804.96   843.6  810.54   863.1  814.67
   872.9  815.74   892.5  816.41  1029.6  818.63  1049.2     818    1059  815.69
#Mann= 3 , 0 , 0
       0     .08       0     429    .045       0   456.4     .05       0
Bank Sta=429,456.4
XS Rating Curve= 0 ,0
Exp/Cntr=0.3,0.1

Type RM Length L Ch R = 1 ,3603    ,45.2,49.5,53.8
XS GIS Cut Line= 4
     1904038.581      632323.999     1904200.039      631946.395
     1904241.706      631844.833     1904502.122      631373.478
#Sta/Elev= 30
       0  894.88    19.6  898.11    29.3  898.55    48.9  897.33    97.8  888.49
   117.3  882.29   146.7  870.94     176  858.75   234.7   833.4   312.9  795.44
   342.2  778.88   381.3  755.05   391.1  750.68   410.7  747.63     429  746.19
   447.3  746.91   474.7  748.94   520.4  749.79   549.8  751.25   598.8  754.94
   657.5  760.97   667.3  763.16   696.7  776.59   716.3   784.3   784.8  807.84
   902.3  838.95   912.1  840.18  1029.6  843.21  1049.2  842.18    1059  839.86
#Mann= 3 , 0 , 0
       0     .08       0   410.7    .045       0   447.3     .05       0
Bank Sta=410.7,447.3
XS Rating Curve= 0 ,0
Exp/Cntr=0.3,0.1

Type RM Length L Ch R = 1 ,3553.5  ,51.6,59.6,67.6
XS GIS Cut Line= 4
     1904050.299      632317.489     1904230.855      631982.419
     1904293.355      631886.933      1904652.73      631393.878
#Sta/Elev= 30
       0  894.02     9.8  894.86    19.5  894.65    48.8  890.99    87.8  882.74
    97.6  879.89   136.6  865.84   165.9  854.15     205  836.92   312.3  785.24
   322.1     780   351.3  759.88   361.1  754.52   370.9  750.88   399.6  747.03
   418.7  746.08  432.79  746.42   524.3   751.1   593.2  756.52   612.8  759.34
   622.7  762.76   642.4  771.55   730.9  812.52   750.6  819.27     908   868.6
   957.3   882.5   986.8  891.59   996.6  894.02  1016.3  895.98  1104.9  897.12
#Mann= 3 , 0 , 0
       0     .08       0   399.6    .045       0  432.79     .05       0
Bank Sta=399.6,432.79
XS Rating Curve= 0 ,0
Exp/Cntr=0.3,0.1

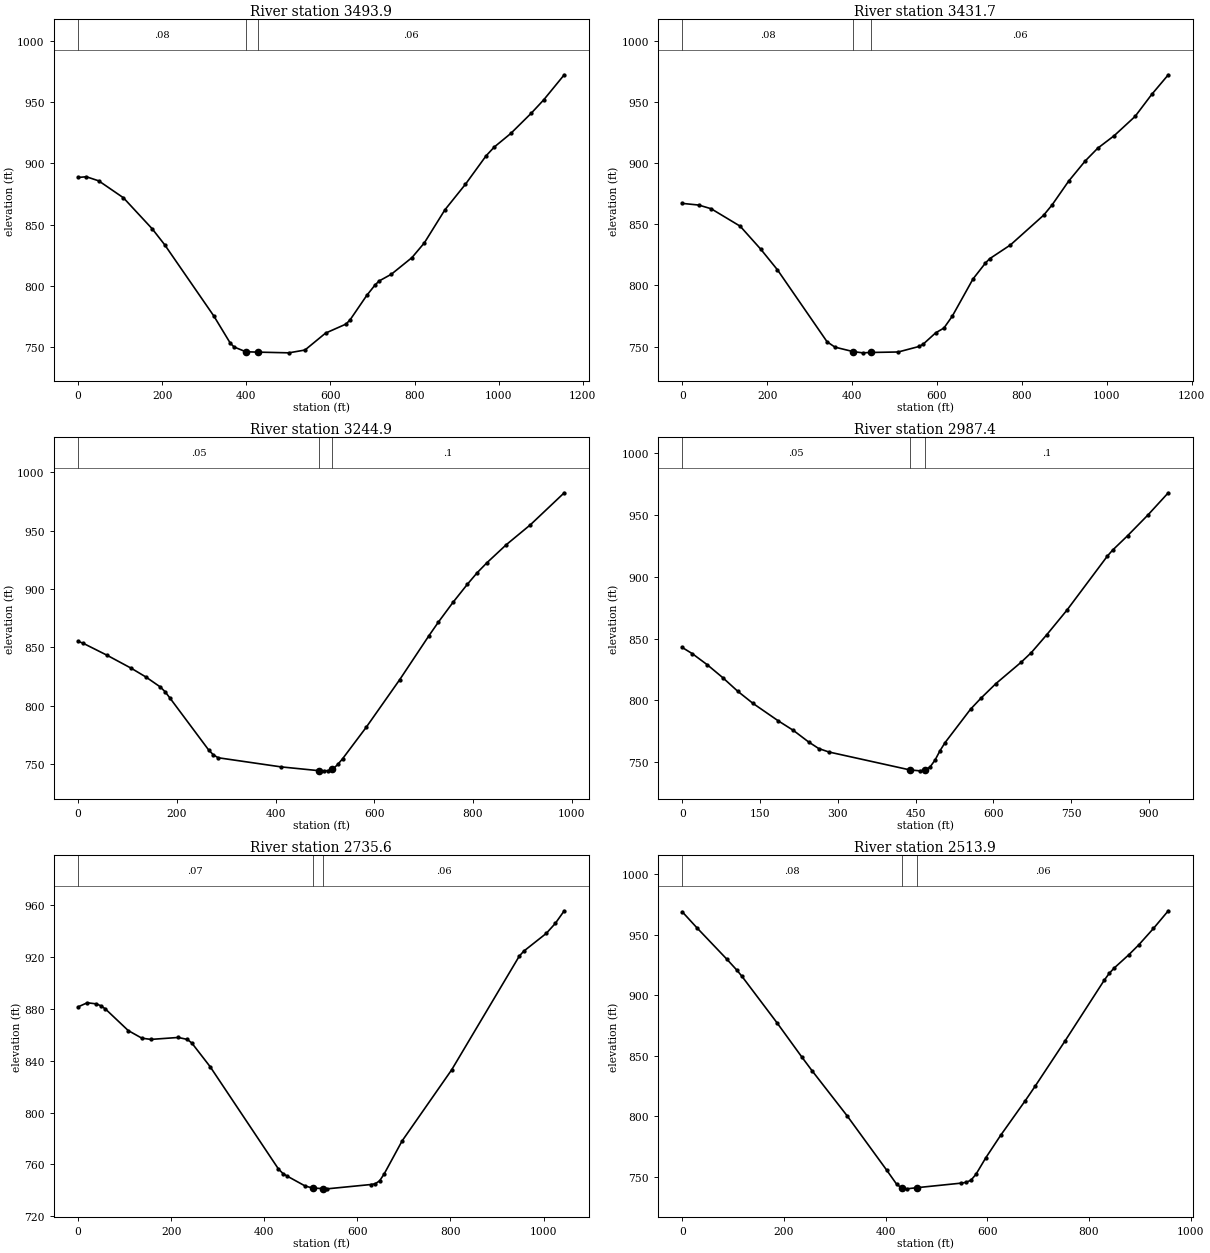
Type RM Length L Ch R = 1 ,3493.9  ,60.3,62.2,66.8
XS GIS Cut Line= 4
      1904058.98      632327.906      1904244.31      632028.426
     1904378.858        631928.6     1904849.779      631501.083
#Sta/Elev= 30
       0  888.44    19.6     889    48.9  885.66   107.6  871.87   176.1  846.56
   205.4  833.74   322.8  775.42   361.5  753.51   370.8  750.25   398.7  746.38
   426.6  746.09   501.1   745.5   539.3  747.79   588.2  761.56   637.1  768.98
   646.9  772.55   686.1  792.24   705.6  800.64   715.4  804.02   744.8  809.58
   793.7  823.12   823.1  835.09     872  862.03   920.9   882.9   969.8  905.99
   989.4  913.23  1028.6  924.26  1077.5  940.83  1106.8  951.61  1155.8  972.11
#Mann= 3 , 0 , 0
       0     .08       0   398.7    .045       0   426.6     .06       0
Bank Sta=398.7,426.6
XS Rating Curve= 0 ,0
Exp/Cntr=0.3,0.1

Type RM Length L Ch R = 1 ,3431.7  ,189.5,186.8,181.3
XS GIS Cut Line= 4
     1904093.702      632354.381     1904282.504      632070.093
     1904417.053      631970.267     1904887.973      631542.749
#Sta/Elev= 30
       0  867.04      39  865.66    68.2  862.65   136.5  848.41   185.3  829.51
   224.3   812.8   341.3     754   359.9  749.66  401.79  746.09   424.8  745.02
   443.6  745.31   508.8  745.72   557.7  750.21   567.5  752.08   596.9  761.34
   616.4  765.26     636  774.91   684.9  805.34   714.3  818.38   724.1  821.86
     773  833.09   851.3   857.4   870.9  865.66     910  885.13   949.1  901.64
   978.5  912.04  1017.6  922.36  1066.6  938.02  1105.7  955.95  1144.8  972.02
#Mann= 3 , 0 , 0
       0     .08       0  401.79    .045       0   443.6     .06       0
Bank Sta=401.79,443.6
XS Rating Curve= 0 ,0
Exp/Cntr=0.3,0.1

Type RM Length L Ch R = 1 ,3244.9  ,247.6,257.5,268
XS GIS Cut Line= 4
     1904104.987      632373.478     1904454.379      632121.742
     1904595.438      632006.725     1904916.619      631817.923
#Sta/Elev= 30
       0  855.05     9.8   853.5    58.7  843.14   107.7  832.01     137  824.63
   166.4  816.04   176.2  811.93     186  806.54   264.2   762.2     274  757.87
   283.8  755.38   411.1  747.56   488.1   744.3   497.7  744.17   507.3   744.4
   514.1  745.45   516.8  745.86   526.4  749.76     536  754.56   583.9  781.51
   651.9  822.38   710.7  859.75   730.3  871.67   759.7  888.46   789.1  904.08
   808.7  913.83   828.3  922.32   867.6   937.8   916.6  954.91   985.2  982.32
#Mann= 3 , 0 , 0
       0     .05       0   488.1    .045       0   514.1      .1       0
Bank Sta=488.1,514.1
XS Rating Curve= 0 ,0
Exp/Cntr=0.3,0.1

Type RM Length L Ch R = 1 ,2987.4  ,256.4,251.7,246.4
XS GIS Cut Line= 3
     1904067.697       632442.67     1904511.079      632327.711
     1904978.241      632221.434
#Sta/Elev= 30
       0  842.93    19.5   837.9    48.7   828.8      78  818.54   107.2  807.41
   136.4  797.65   185.2  783.51   214.4  775.74   243.6  766.44   263.1   761.1
   282.6   758.3   438.6   743.8     458  743.02   467.8  743.73   477.6  746.01
   487.4  751.71   497.2  759.46   506.9  765.96   555.8   792.9   575.4  801.62
   604.7  813.63   653.6  831.02   673.2  838.83   702.5  853.07   741.6  873.08
   819.8  916.99   829.6  921.67   858.9  933.52     898  950.27   937.1  968.18
#Mann= 3 , 0 , 0
       0     .05       0   438.6    .045       0   467.8      .1       0
Bank Sta=438.6,467.8
XS Rating Curve= 0 ,0
Exp/Cntr=0.3,0.1

Type RM Length L Ch R = 1 ,2735.6  ,231.9,221.8,211.6
XS GIS Cut Line= 4
     1904087.626      632837.888     1904489.101      632594.833
     1904632.331      632525.388     1904973.042      632286.673
#Sta/Elev= 30
       0  881.48    19.6   884.6    39.1  883.75    48.9  882.26    58.7  879.78
   107.6  863.19   136.9  857.32   156.4  856.38   215.1  857.87   234.7  856.35
   244.4  853.51   283.6  835.36   430.2  756.64     440  753.04   449.8  750.92
     488  743.38   503.8  741.88   525.5  741.43   534.9  741.24   628.5  744.55
   638.2  745.13   647.8  747.43   657.5  752.69   696.2  778.22   802.6  832.94
   947.8  920.48   957.4  924.33  1005.8  938.03  1025.2  945.72  1044.5  955.48
#Mann= 3 , 0 , 0
       0     .07       0   503.8    .045       0   525.5     .06       0
Bank Sta=503.8,525.5
XS Rating Curve= 0 ,0
Exp/Cntr=0.3,0.1

Type RM Length L Ch R = 1 ,2513.9  ,323,326.5,330.3
XS GIS Cut Line= 3
     1904415.474      633056.881     1904706.115      632685.978
     1905019.306      632315.554
#Sta/Elev= 30
       0  968.92    29.4  955.48    88.4  929.51     108  920.51   117.8  915.48
   186.5  877.28   235.6  848.87   255.2  837.86     324  800.75   402.5  755.54
   422.1   743.9     432  740.95   441.8  740.22   461.4  741.16   548.8  744.93
   558.5  745.57   568.2  747.39   577.9   752.2   597.3  765.87   626.4  784.34
     675  813.04   694.4  824.96   752.6  861.92   830.2  912.35   839.9  917.96
   849.6  922.37   878.7  933.44   898.1  941.54   927.2  955.17   956.3  969.72
#Mann= 3 , 0 , 0
       0     .08       0     432    .045       0   461.4     .06       0
Bank Sta=432,461.4
XS Rating Curve= 0 ,0
Exp/Cntr=0.3,0.1

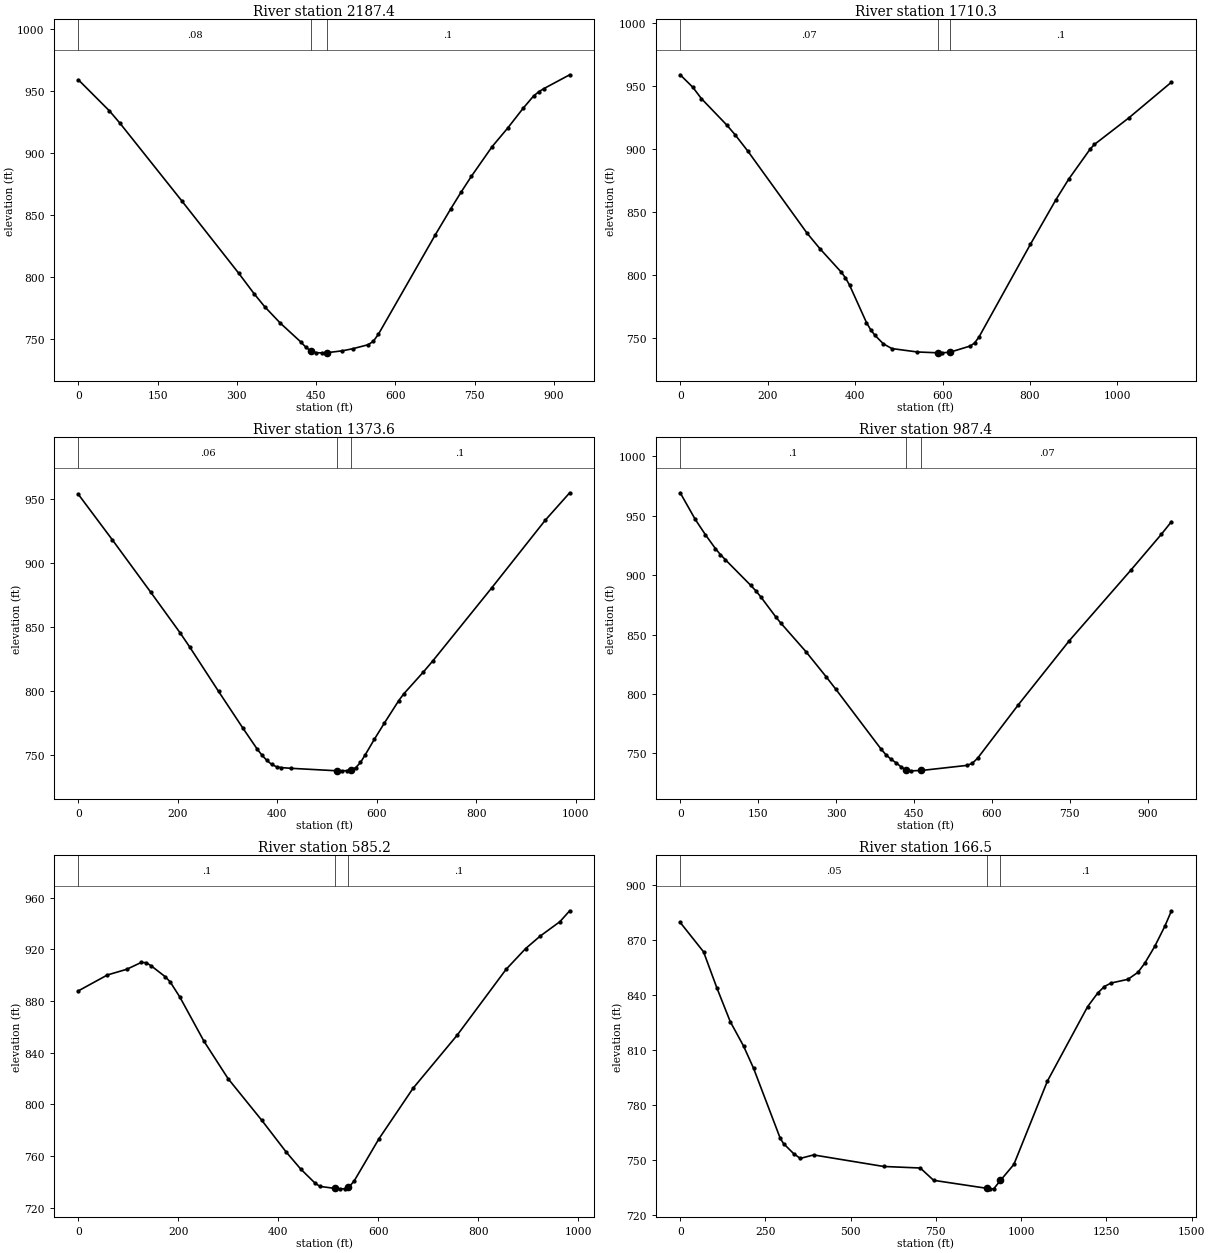
Type RM Length L Ch R = 1 ,2187.4  ,465.5,477.1,487
XS GIS Cut Line= 3
     1904634.779       633190.63      1904944.63      632850.233
     1905268.382      632510.094
#Sta/Elev= 30
       0  959.13    58.8  934.09    78.4  924.31   195.9   861.5   303.6  803.23
     333  786.58   352.6  776.36     382   763.2   421.1   747.9   430.9  743.53
   440.7  740.46   450.5  739.27   460.3   739.2   470.1  739.31   499.4  740.82
     519  742.48   548.4  745.74   558.1  748.46   567.9  754.25   675.5  834.27
   704.9  855.29   724.4  868.72     744  881.53   783.1  905.34   812.5  920.25
   841.8  936.24   861.4  946.04   871.2  949.47     881  952.07   929.9  963.21
#Mann= 3 , 0 , 0
       0     .08       0   440.7    .045       0   470.1      .1       0
Bank Sta=440.7,470.1
XS Rating Curve= 0 ,0
Exp/Cntr=0.3,0.1

Type RM Length L Ch R = 1 ,1710.3  ,326.8,336.7,345.3
XS GIS Cut Line= 4
     1904702.405      633270.268     1905229.119      633141.708
     1905334.753      633104.965     1905778.164      632950.735
#Sta/Elev= 30
       0  958.99      29  949.02    48.4  940.07   106.5  919.04   125.9  911.16
   154.9  898.19   290.4   832.9   319.5  820.71   367.9   802.2   377.6  797.67
   387.3  791.72     426  761.94   435.7  756.15   445.4  751.79   464.7     745
   484.1  741.26   542.2  738.55   588.8   737.9   598.1  737.86   616.7  738.34
   663.8  743.34   673.6  745.86   683.4  750.51   800.7  824.05   859.4  859.74
   888.8  876.15   937.6  899.93   947.4  903.62  1025.7  924.63  1123.5  953.13
#Mann= 3 , 0 , 0
       0     .07       0   588.8    .045       0   616.7      .1       0
Bank Sta=588.8,616.7
XS Rating Curve= 0 ,0
Exp/Cntr=0.3,0.1

Type RM Length L Ch R = 1 ,1373.6  ,388.2,386.2,384.6
XS GIS Cut Line= 4
     1904700.907      633421.221     1905128.424      633429.902
     1905295.525      633440.753      1905688.32      633447.263
#Sta/Elev= 30
       0  953.52      68  918.13   145.8  876.82   204.1  845.46   223.5  834.33
   281.8  799.45   330.4   770.9   359.6  754.26   369.3  749.45     379  745.43
   388.7  742.28   398.4   740.5   408.2  739.82   427.6  739.28   520.6  737.32
   529.9   737.3   539.2  737.46   547.9  738.04   557.8  739.82   567.2  743.85
   576.4   749.6   595.1     762   614.7  774.34   644.2  792.26     654  797.42
   693.3  814.44   712.9  823.42   830.8  880.28   938.8  933.37   987.9  954.81
#Mann= 3 , 0 , 0
       0     .06       0   520.6    .045       0   547.9      .1       0
Bank Sta=520.6,547.9
XS Rating Curve= 0 ,0
Exp/Cntr=0.3,0.1

Type RM Length L Ch R = 1 ,987.4   ,411.5,402.1,389.5
XS GIS Cut Line= 3
     1904659.254      633754.148     1905113.752      633735.447
     1905604.365      633758.914
#Sta/Elev= 30
       0  969.35      29  946.95    48.4  934.15    67.8   922.4    77.4  917.37
    87.1  912.94   135.5  891.56   145.2  887.02   154.8  881.94   183.9  864.96
   193.6  859.74     242  835.66   280.7  814.67     300   803.8   387.1  753.42
   396.8   748.5   406.5  744.87   416.2  741.89   425.8  738.44   435.5  735.89
   445.2  735.25   464.7  735.56   553.1  739.88   562.9  741.76   572.8  745.89
   651.4     791   749.6  844.95   867.5  904.03   926.4  934.28   946.1  945.05
#Mann= 3 , 0 , 0
       0      .1       0   435.5    .045       0   464.7     .07       0
Bank Sta=435.5,464.7
XS Rating Curve= 0 ,0
Exp/Cntr=0.3,0.1

Type RM Length L Ch R = 1 ,585.2   ,422,418.8,415.5
XS GIS Cut Line= 4
     1904722.608      634148.218     1905157.114      634136.481
     1905304.206      634059.242     1905650.866       633899.06
#Sta/Elev= 30
       0  887.85      58  900.14    96.6  904.52   125.6  909.82   135.2  909.66
   144.9  907.41   173.9   898.7   183.5  894.78   202.8  883.09   251.1  848.85
   299.4  819.84     367   787.5   415.4  763.14   444.4  749.98   473.8  738.78
   483.5   736.4   512.8  734.89   522.6  734.54   532.4  734.61   538.3  735.63
   542.2   736.3   551.9  740.85   600.8  773.08   669.3  812.37   757.5  853.46
   855.4  904.45   894.6  920.59   923.9   930.3   963.1  941.39   982.7  949.83
#Mann= 3 , 0 , 0
       0      .1       0   512.8    .045       0   538.3      .1       0
Bank Sta=512.8,538.3
XS Rating Curve= 0 ,0
Exp/Cntr=0.3,0.1

Type RM Length L Ch R = 1 ,166.5   ,173.6,166.5,159.4
XS GIS Cut Line= 4
     1904516.445      634616.968      1905377.99       634493.27
     1905497.348      634406.465     1905744.744      634063.583
#Sta/Elev= 30
       0   879.6    68.5  863.59   107.6  843.92   146.7  825.59   185.8  812.25
   215.2  800.12   293.4  761.97   303.2  759.08   332.5  753.67   352.1  751.03
   391.2  752.92   596.6  746.64   704.1   745.8   743.2  739.09   899.9  734.72
   909.7  734.45   919.6  734.49   939.2  739.02   978.6  747.74    1077  793.17
    1195  833.75  1224.5  841.11  1244.1  844.68  1263.8  846.58    1313  848.59
  1342.4  852.39  1362.1  857.26  1391.6  866.49  1421.1  877.43  1440.8  885.94
#Mann= 3 , 0 , 0
       0     .05       0   899.9    .045       0   939.2      .1       0
Bank Sta=899.9,939.2
XS Rating Curve= 0 ,0
Exp/Cntr=0.3,0.1

Chan Stop Cuts=-1
Use User Specified Reach Order=0
Composite Channel Slope=5